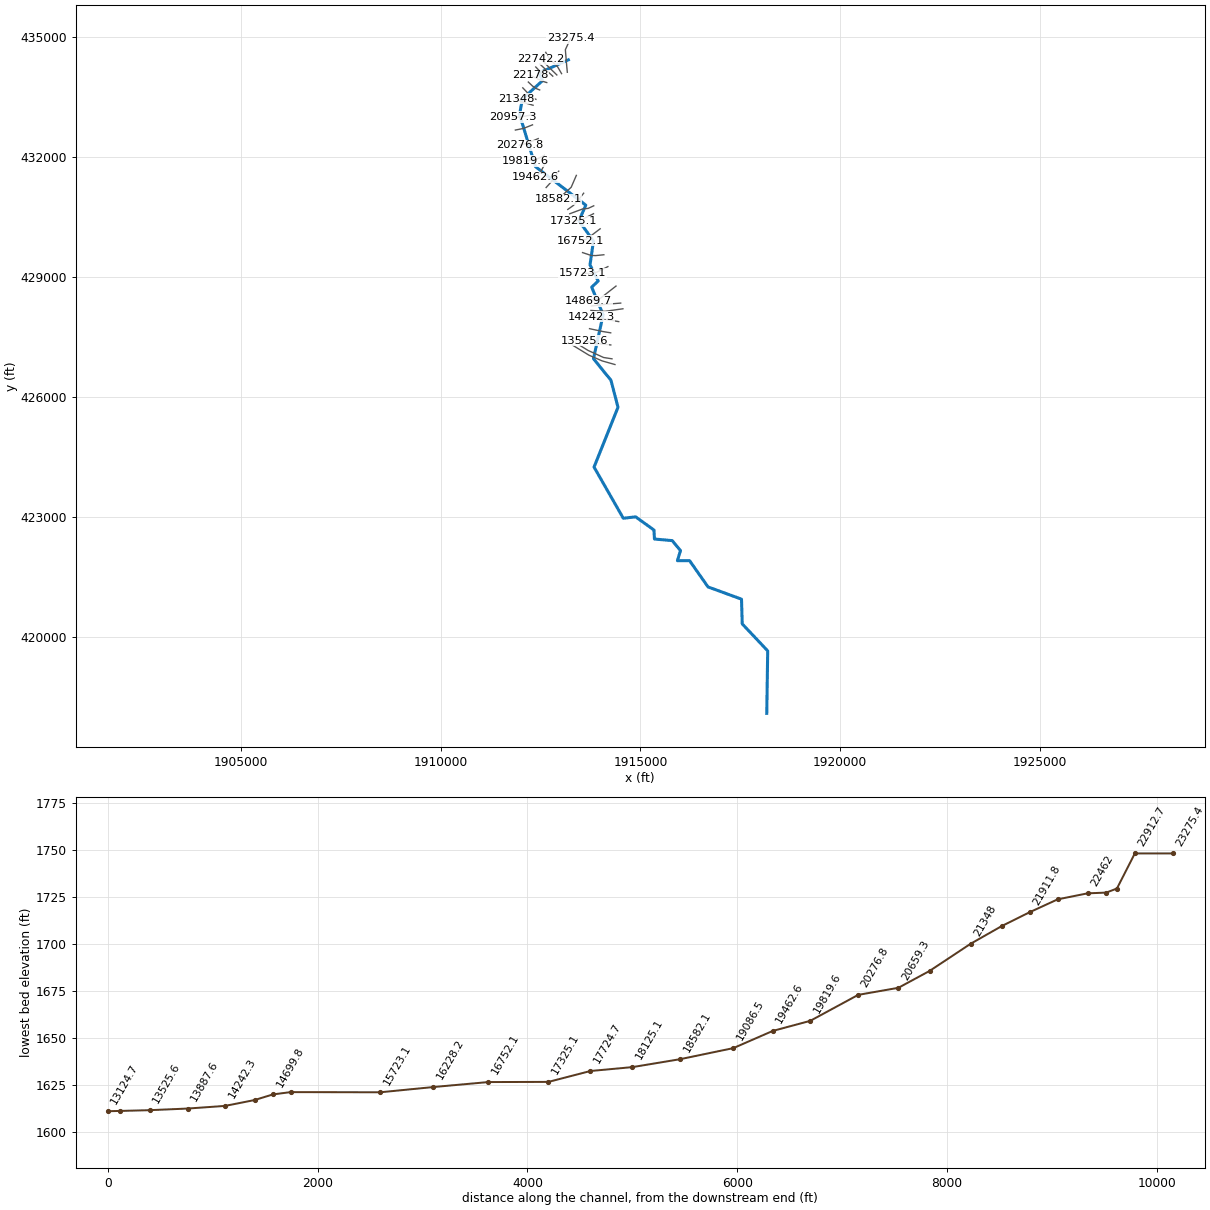
--- HAZELRUN.prj (project) ---

Proj Title=HAZELRUN
Current Plan=p01
Default Exp/Contr=0,0
English Units
Geom File=g01
Flow File=f01
Plan File=p01
BEGIN DESCRIPTION:
END DESCRIPTION:
DSS Export Rating Curves= 0
DSS Export Rating Curve Sorted= 0
DSS Export Volume Flow Curves= 0
DXF OffsetX= 0
DXF OffsetY= 0
DXF ScaleX= 0
DXF ScaleY= 0

--- HAZELRUN.p01 (plan) ---

Plan Title=Floodplain
Program Version=4.00
Geom File=g01
Flow File=f01
K Sum by GR=0
Std Step Tol=0.01
Critical Tol=0.01
Num of Std Step Trials=20
Max Error Tol=0.3
Flow Tol Ratio=0.001
Split Flow NTrial=30
Split Flow Tol=0.02
Split Flow Ratio=0.02
Log Output Level=0
Friction Slope Method=1
Unsteady Friction Slope Method=2
Unsteady Bridges Friction Slope Method=1
Global Log Level=0
CheckData=False
Run HTab=0
Run UNet=0
Run PostProcess=0
UNET Theta=0
UNET Theta Warmup=0
UNET ZTol=0
UNET ZSATol=0
UNET MxIter=0
UNET MaxInSteps=0
UNET DtIC=0
UNET DtMin=0
UNET MaxCRTS=0
UNET WFStab=0
UNET SFStab=0
UNET WFX=0
UNET SFX=0
UNET DSS MLevel=0
UNET DZMax Abort=0
UNET Convert EG Bridges=0
UNET Use Existing IB Tables=0
UNET Froude Limit=0
UNET Froude Power=0
Write IC File=0
Echo Input=False
Echo Output=False
Write Detailed=0

--- HAZELRUN.f01 (steady flow) ---

Flow Title=NFF Regression Equation
Program Version=4.00
Number of Profiles=1
Profile Names=P100yr
River Rch & RM=HAZELRUN,Main      ,23275.4
518.2390
River Rch & RM=HAZELRUN,Main      ,20957.3
560.1029
River Rch & RM=HAZELRUN,Main      ,18125.1
613.8987
River Rch & RM=HAZELRUN,Main      ,14869.7
662.7180
River Rch & RM=HAZELRUN,Main      ,14525.9
841.0247
River Rch & RM=HAZELRUN,Main      ,12276.3
910.5224
River Rch & RM=HAZELRUN,Main      ,9506
965.4316
River Rch & RM=HAZELRUN,Main      ,8726.2
1074.196
River Rch & RM=HAZELRUN,Main      ,4743
1185.766
River Rch & RM=HAZELRUN,Main      ,135.1
1273.891
Boundary for River Rch & Prof#=HAZELRUN,Main      ,1
Up Type=0
Dn Type=3
Dn Slope=0.040756

--- HAZELRUN.g01 (geometry) ---

Geom Title=USGS 10m DEM
Program Version=4.10

River Reach=HAZELRUN        ,Main
Reach XY= 30
     1913197.861       434440.15     1912457.562      434107.716
     1912554.133      433922.169     1912048.491      433461.015
     1911976.518      433073.361     1912373.819      431770.748
     1913633.281      430807.293     1913463.142       430411.46
     1913826.336      429910.765     1913739.531      429313.543
     1913943.697      428909.376     1913781.197      428755.904
     1914068.403      428066.164     1913825.946      426967.319
     1914263.446       426428.43     1914439.782      425753.309
     1913840.477      424257.475     1914571.727      422977.961
     1914880.755      423013.552     1915339.088      422683.691
     1915352.109      422458.864     1915796.553      422418.934
     1916002.933      422169.368     1915925.893      421916.547
     1916230.798      421917.632     1916691.952      421261.165
     1917529.626      420955.175     1917548.072      420336.685
     1918185.008      419661.772     1918161.467      418099.647

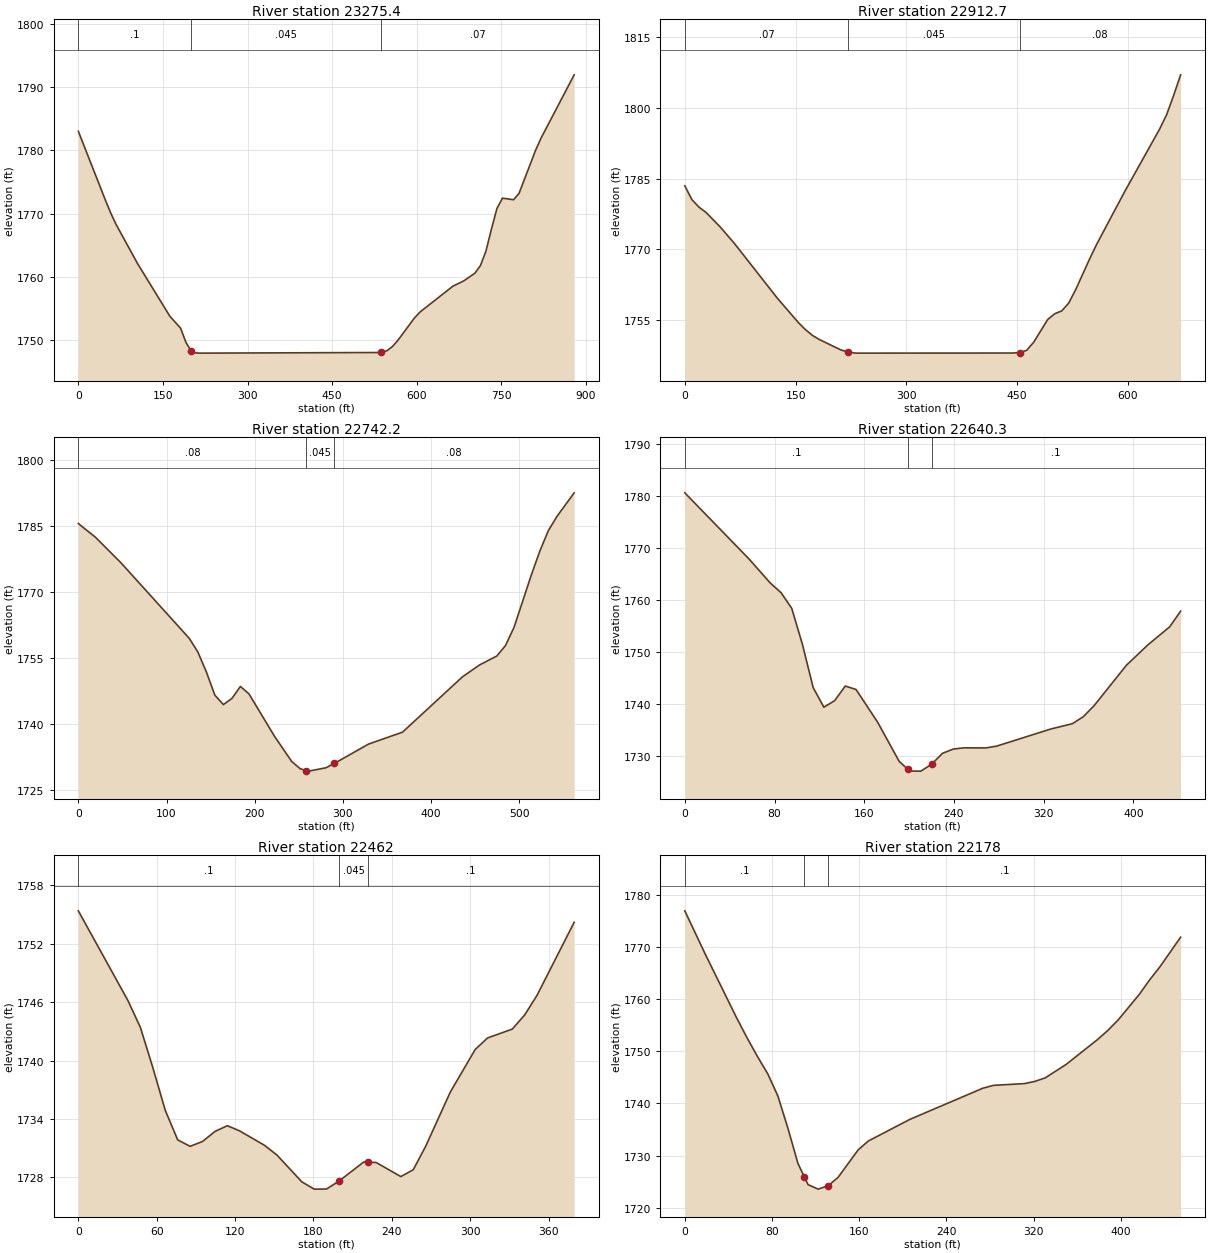
Type RM Length L Ch R = 1 ,23275.4 ,345.8,362.7,379.5
XS GIS Cut Line= 4
     1913171.915      434128.924     1913153.092      434328.347
      1913122.71       434692.93     1913252.918      434977.219
#Sta/Elev= 30
       0 1783.03    47.7 1772.22    57.2 1770.17    66.8 1768.34   104.9 1762.15
   162.2 1753.83   181.2 1751.95   190.8 1749.69   200.3 1748.26   209.9 1748.01
   219.6    1748   537.3  1748.1   546.9 1748.38   556.5 1749.02   566.2    1750
   595.5 1753.52   605.2 1754.46   663.9 1758.57   683.4 1759.42     703 1760.63
   712.7 1761.83   722.5 1764.12   732.3 1767.62     742 1770.85   751.8 1772.47
   771.4 1772.22   781.1 1773.22   810.4 1780.02   820.2 1781.96   878.8 1791.94
#Mann= 3 , 0 , 0
       0      .1       0   200.3    .045       0   537.3     .07       0
Bank Sta=200.3,537.3
XS Rating Curve= 0 ,0
Exp/Cntr=0.3,0.1

Type RM Length L Ch R = 1 ,22912.7 ,172,170.5,163.8
XS GIS Cut Line= 4
     1913027.818      434094.201     1912921.662      434277.276
     1912730.255       434454.36     1912631.984      434627.187
#Sta/Elev= 30
       0  1783.5     9.6 1780.58    19.2 1778.98    28.9 1777.83    48.1 1774.74
    67.3 1771.24     125  1759.7   153.9 1754.44   163.5 1752.94   173.2  1751.7
   182.8 1750.82   211.6 1748.64   221.3 1748.22   230.9 1747.98   443.4    1748
   453.1 1748.11   462.7 1748.56   472.4 1750.32   491.3 1755.12   500.8 1756.35
   510.2 1756.94   519.7  1758.6   529.2 1761.48   548.1 1768.01   557.6 1771.09
   595.5 1782.28   642.8 1795.55   652.3 1798.62   661.7 1802.66   671.2 1807.06
#Mann= 3 , 0 , 0
       0     .07       0   221.3    .045       0   453.1     .08       0
Bank Sta=221.3,453.1
XS Rating Curve= 0 ,0
Exp/Cntr=0.3,0.1

Type RM Length L Ch R = 1 ,22742.2 ,100.8,101.9,108.3
XS GIS Cut Line= 3
     1912909.762      434061.215     1912619.832      434345.937
     1912510.457      434457.049
#Sta/Elev= 30
       0 1785.54    19.4 1782.43    48.4 1776.62   125.8 1759.48   135.4 1756.44
   145.1 1751.92   154.8  1746.6   164.5 1744.44   174.2 1745.84   183.8 1748.56
   193.5 1746.88   222.5 1737.24   241.9 1731.56   251.6 1729.88  258.55 1729.47
   261.2 1729.34   280.6 1730.09   290.3 1731.08     329 1735.47   367.7 1738.19
   435.6 1750.74   455.1 1753.45   474.6 1755.47   484.3 1757.81   494.1 1761.97
   513.6 1773.78   523.3 1779.24     533 1783.92   542.8 1787.16   562.3 1792.51
#Mann= 3 , 0 , 0
       0     .08       0  258.55    .045       0   290.3     .08       0
Bank Sta=258.55,290.3
XS Rating Curve= 0 ,0
Exp/Cntr=0.3,0.1

Type RM Length L Ch R = 1 ,22640.3 ,179.9,178.3,176.7
XS GIS Cut Line= 3
     1912807.946      434031.617     1912688.155      434140.992
     1912486.332      434335.002
#Sta/Elev= 30
       0 1780.69    57.2 1767.99    76.3 1763.34    85.9 1761.48    95.4 1758.47
     105 1751.48   114.5 1743.24     124 1739.47   133.6 1740.72   143.1 1743.54
   152.7 1742.88   171.9 1736.62   191.2 1729.06   198.8 1727.55   200.8 1727.19
   210.5 1727.18   220.1  1728.5   229.8  1730.6   239.4 1731.42   249.1 1731.66
   268.4 1731.64     278 1731.98   326.3 1735.27   345.6  1736.3   355.3 1737.62
   364.9 1739.73   393.9 1747.55   413.2 1751.49   432.5 1754.94   442.2 1757.94
#Mann= 3 , 0 , 0
       0      .1       0   198.8    .045       0   220.1      .1       0
Bank Sta=198.8,220.1
XS Rating Curve= 0 ,0
Exp/Cntr=0.3,0.1

Type RM Length L Ch R = 1 ,22462   ,274.2,284,293.4
XS GIS Cut Line= 3
     1912662.113      434006.877     1912538.415      434095.419
     1912382.165      434260.783
#Sta/Elev= 30
       0 1755.39      38 1746.16    47.5 1743.41      57 1739.29    66.6 1734.86
    76.1 1731.84    85.6 1731.18    95.1 1731.68   104.6 1732.71   114.1  1733.3
   123.6 1732.76   142.6 1731.28   152.1 1730.28   171.1 1727.53   180.6 1726.78
     190 1726.79   199.5  1727.6   218.5 1729.57   221.9 1729.55     228 1729.52
   246.9 1728.07   256.4 1728.77   265.9 1731.18   284.8 1736.76   303.8 1741.13
   313.3 1742.32   332.2 1743.23   341.7 1744.68   351.2 1746.71   379.6 1754.21
#Mann= 3 , 0 , 0
       0      .1       0   199.5    .045       0   221.9      .1       0
Bank Sta=199.5,221.9
XS Rating Curve= 0 ,0
Exp/Cntr=0.3,0.1

Type RM Length L Ch R = 1 ,22178   ,270,266.3,261.7
XS GIS Cut Line= 4
     1912656.905       433871.46     1912583.988      433893.596
     1912499.353      433930.054      1912241.54      434055.054
#Sta/Elev= 30
       0  1776.9      19 1768.51    47.6 1756.39    57.2 1752.55    66.7 1748.99
    76.2 1745.65    85.4 1741.44    94.6 1735.27   103.8 1728.52   109.8  1725.9
   113.1 1724.46   122.3  1723.6   131.5 1724.24   140.7 1725.87   159.1 1731.13
   168.4 1732.82   206.6 1736.97   273.4 1742.92     283 1743.47   311.6 1743.81
   321.2 1744.23   330.7 1744.91   349.8 1747.47   378.5 1752.22     388 1753.97
   397.6 1756.01   416.7 1760.82   426.2  1763.6   435.8 1766.15   454.9 1771.85
#Mann= 3 , 0 , 0
       0      .1       0   109.8    .045       0   131.5      .1       0
Bank Sta=109.8,131.5
XS Rating Curve= 0 ,0
Exp/Cntr=0.3,0.1

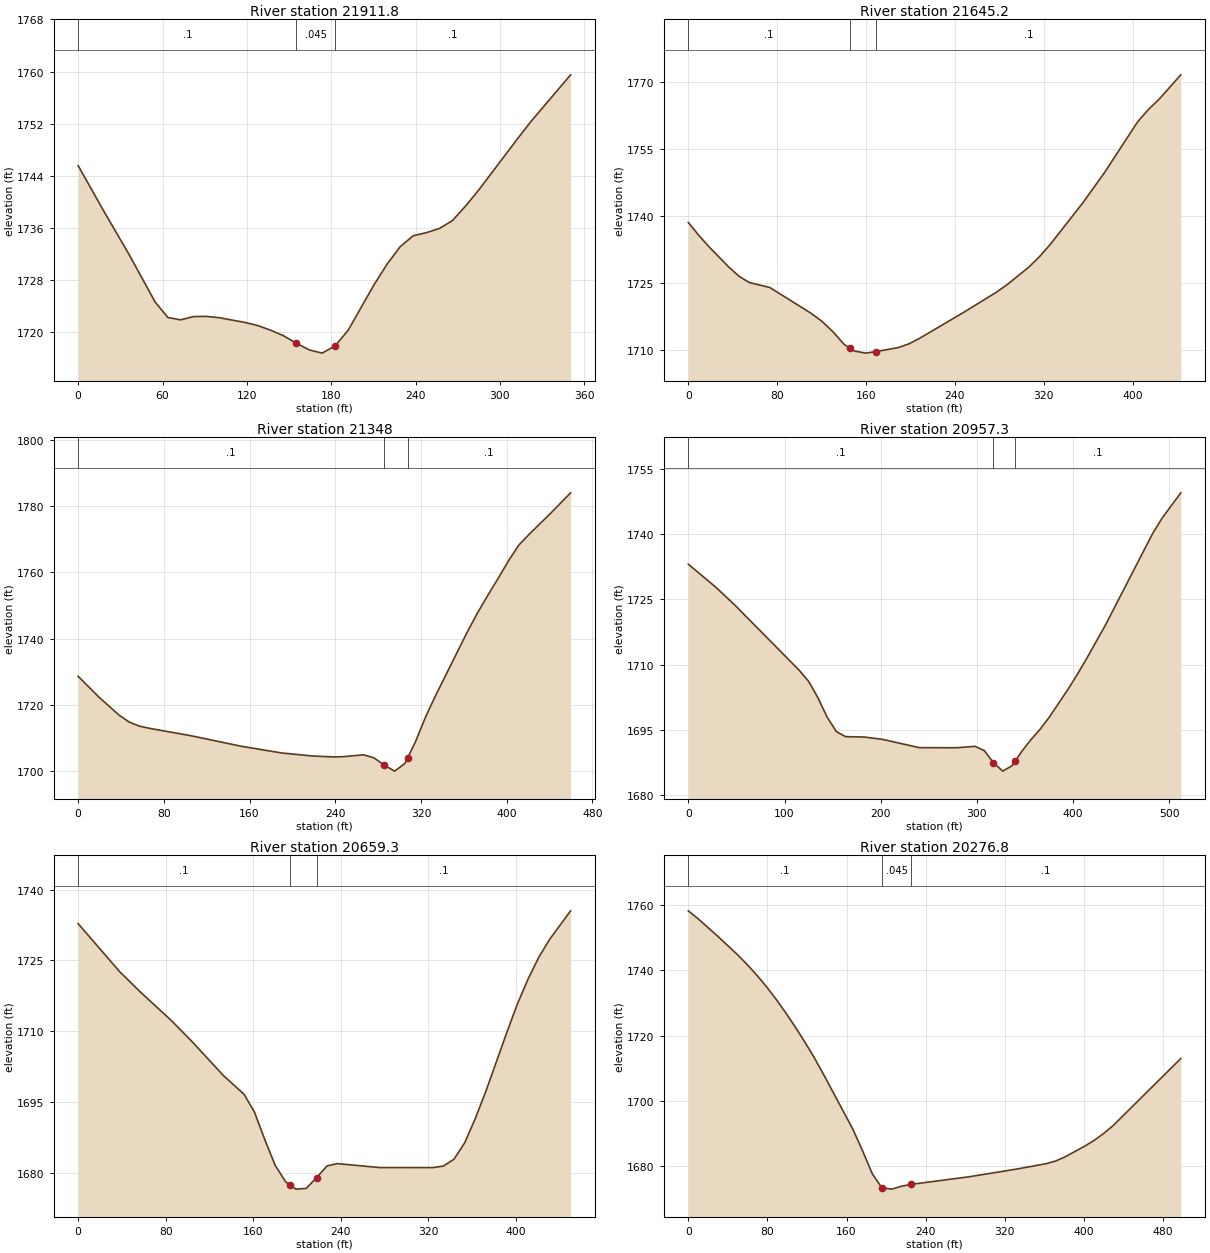
Type RM Length L Ch R = 1 ,21911.8 ,271.9,266.5,261.6
XS GIS Cut Line= 4
     1912479.821      433686.565     1912378.512      433727.882
      1912297.53      433788.127     1912195.967      433884.481
#Sta/Elev= 30
       0 1745.55    18.2 1738.59    36.5 1731.81    54.7 1724.64    63.8 1722.25
    72.9 1721.89    82.1 1722.39    91.2 1722.42   100.3 1722.22   118.6 1721.49
   127.8 1721.01   136.9  1720.3   146.1 1719.45   155.3 1718.28   164.5 1717.27
   173.6 1716.78   182.8  1717.9     192 1720.27   210.3 1727.21   219.7 1730.41
     229  1733.1   238.3 1734.79   247.7 1735.27     257 1735.91   266.3 1737.13
   275.7 1739.38     285 1741.83     313 1749.81   322.3 1752.38   350.3 1759.49
#Mann= 3 , 0 , 0
       0      .1       0   155.3    .045       0   182.8      .1       0
Bank Sta=155.3,182.8
XS Rating Curve= 0 ,0
Exp/Cntr=0.3,0.1

Type RM Length L Ch R = 1 ,21645.2 ,289.3,297.2,304.8
XS GIS Cut Line= 3
     1912386.071       433452.19     1912293.443      433491.771
     1912057.332      433740.035
#Sta/Elev= 30
       0 1738.57     9.2 1735.76    18.3 1733.22    36.6 1728.57    45.8 1726.53
    54.9 1725.16    73.3 1724.06   110.5  1718.3   120.3  1716.5   130.1  1714.2
   139.9 1711.45  145.24 1710.52   149.7 1709.87   159.5 1709.41   169.2 1709.76
   188.8 1710.64   198.6 1711.48   208.4 1712.75   247.6 1718.47   276.9 1722.94
   286.7 1724.64   306.3 1728.56   316.1 1730.94   325.9  1733.7   355.2 1742.97
   374.8 1749.76   404.2 1760.93     414 1763.74   423.8 1766.07   443.3 1771.51
#Mann= 3 , 0 , 0
       0      .1       0  145.24    .045       0   169.2      .1       0
Bank Sta=145.24,169.2
XS Rating Curve= 0 ,0
Exp/Cntr=0.3,0.1

Type RM Length L Ch R = 1 ,21348   ,376,390.7,404.5
XS GIS Cut Line= 3
      1912314.97      433304.132     1912059.762      433380.521
     1911886.151       433465.59
#Sta/Elev= 30
       0 1728.63      19 1722.47    38.1 1716.94    47.6 1714.82    57.1 1713.59
    66.6 1712.92   104.7 1710.72   152.2 1707.51   190.3 1705.46   218.8 1704.56
   237.8 1704.29   247.4 1704.36   266.4 1704.92   276.1 1704.01   285.7 1701.81
   295.4 1699.99   305.1 1702.32   307.7 1704.06   314.7 1708.75   324.4 1716.42
   334.1  1723.1   363.1 1741.94   372.7 1747.72   382.4  1753.1   392.1 1758.24
   401.7 1763.52   411.4 1768.29   421.1 1771.57   440.4 1777.68   459.7 1784.07
#Mann= 3 , 0 , 0
       0      .1       0   285.7    .045       0   307.7      .1       0
Bank Sta=285.7,307.7
XS Rating Curve= 0 ,0
Exp/Cntr=0.3,0.1

Type RM Length L Ch R = 1 ,20957.3 ,292.9,298.1,302.3
XS GIS Cut Line= 3
      1912314.97      433066.285     1911964.276      433007.257
     1911808.026      433008.993
#Sta/Elev= 30
       0 1733.09    28.8 1727.75    48.1 1723.75   115.3 1708.71     125 1706.19
   134.6 1702.46   144.2    1698   153.8 1694.66   163.4 1693.48   182.6  1693.4
   201.8 1692.85   240.3 1690.95   278.7 1690.93     298 1691.25   307.6 1690.28
   317.2 1687.48   326.8 1685.56   336.4 1686.78  339.96 1687.88     346  1689.9
   355.6 1692.64   365.4 1695.11   375.2 1697.95   394.7 1704.36   404.5 1707.84
   414.2 1711.48   433.8  1719.2   482.6 1740.12   492.4 1743.64   511.9 1749.48
#Mann= 3 , 0 , 0
       0      .1       0   317.2    .045       0  339.96      .1       0
Bank Sta=317.2,339.96
XS Rating Curve= 0 ,0
Exp/Cntr=0.3,0.1

Type RM Length L Ch R = 1 ,20659.3 ,381.3,382.4,382.6
XS GIS Cut Line= 3
     1912301.082      432814.549     1912071.915      432724.271
     1911872.262       432684.34
#Sta/Elev= 30
       0  1732.8    37.9 1722.63    56.8 1718.33    85.3 1712.25   104.2 1707.79
   132.6 1700.65   151.6 1696.66     161 1692.93   170.5 1687.08     180 1681.62
   189.5 1678.14  193.47 1677.47   198.9 1676.58   208.4 1676.74   217.9 1679.03
   227.4  1681.5   236.8 1681.98   275.4 1681.15   323.9 1681.14   333.6 1681.46
   343.3  1682.9     353 1686.33   362.6  1691.4   372.4 1697.24   391.7 1709.81
   401.4 1715.84   411.1  1721.1   420.8 1725.66   430.5 1729.38   449.9 1735.51
#Mann= 3 , 0 , 0
       0      .1       0  193.47    .045       0   217.9      .1       0
Bank Sta=193.47,217.9
XS Rating Curve= 0 ,0
Exp/Cntr=0.3,0.1

Type RM Length L Ch R = 1 ,20276.8 ,462.7,457.2,451.3
XS GIS Cut Line= 3
     1912443.443      432470.799     1912200.387      432366.632
     1911974.693      432305.868
#Sta/Elev= 30
       0 1758.29     9.8 1755.87    29.4 1750.59      49 1745.04    58.8 1742.03
    68.6 1738.79    78.4 1735.24    88.2 1731.38    97.9 1727.25   107.7 1722.85
   117.5 1718.18   127.3 1713.26   137.1  1707.9   166.5  1691.2   176.3 1684.58
   186.1 1677.56   195.9  1673.2   205.7 1672.84   215.5 1673.72   225.3  1674.3
   283.9 1676.63   332.6 1679.02   361.8 1680.64   371.6 1681.46   381.3 1682.78
   400.8 1685.99   410.5 1687.79   420.3 1689.96     430 1692.42   498.2 1712.95
#Mann= 3 , 0 , 0
       0      .1       0   195.9    .045       0   225.3      .1       0
Bank Sta=195.9,225.3
XS Rating Curve= 0 ,0
Exp/Cntr=0.3,0.1

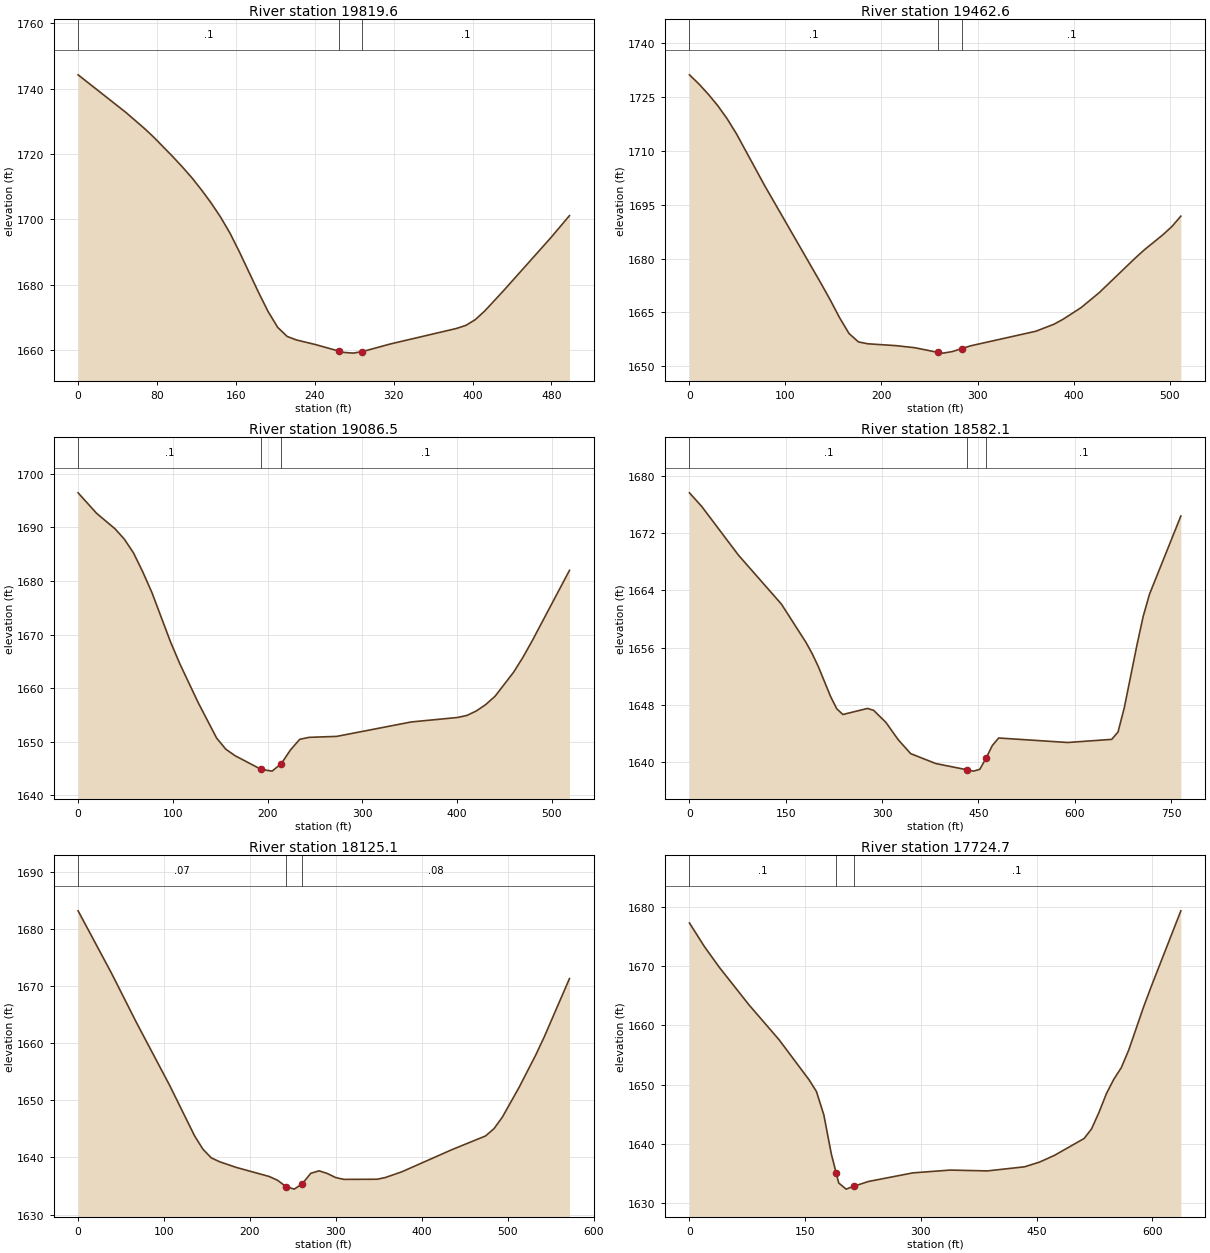
Type RM Length L Ch R = 1 ,19819.6 ,335.6,357,378
XS GIS Cut Line= 3
     1912591.012      432045.451      1912400.04      431953.437
     1912117.054      431910.035
#Sta/Elev= 30
       0 1744.25    48.2  1732.8    67.4 1727.79    77.1 1725.04    96.4 1719.08
     106 1715.95   115.6 1712.65   125.3 1708.95   134.9 1705.01   144.5 1700.68
   154.2 1695.68   163.8 1689.88   183.1 1677.56   192.7 1671.76   202.4 1666.92
     212 1664.14   221.5 1663.06   240.6 1661.66  264.83 1659.62   269.2 1659.26
   278.8 1659.03   288.3  1659.5     317 1661.86   383.8 1666.59   393.3 1667.54
   402.8 1669.29   412.4 1671.95   431.5 1678.17   479.2 1694.31   498.3 1701.13
#Mann= 3 , 0 , 0
       0      .1       0  264.83    .045       0   288.3      .1       0
Bank Sta=264.83,288.3
XS Rating Curve= 0 ,0
Exp/Cntr=0.3,0.1

Type RM Length L Ch R = 1 ,19462.6 ,378.2,376.1,373.9
XS GIS Cut Line= 3
     1912653.512      431918.715     1912497.262      431625.312
     1912365.318      431503.785
#Sta/Elev= 30
       0 1731.15     9.8 1728.62    19.6 1725.75    29.3 1722.63    39.1 1718.98
    48.9 1714.75    78.2 1700.37   136.9 1673.14   146.6  1668.5   156.4 1663.52
   166.2 1659.14     176  1656.8   185.8 1656.28   215.1 1655.76   234.6 1655.19
  258.79 1653.88     264 1653.68   273.8 1654.11   283.5 1654.94   293.3 1655.74
   360.7 1659.77   379.6 1661.72   389.1  1663.1   407.9 1666.35   426.8 1670.52
   464.6 1680.22     474 1682.49   492.9 1686.58   502.4  1688.9   511.8 1691.81
#Mann= 3 , 0 , 0
       0      .1       0  258.79    .045       0   283.5      .1       0
Bank Sta=258.79,283.5
XS Rating Curve= 0 ,0
Exp/Cntr=0.3,0.1

Type RM Length L Ch R = 1 ,19086.5 ,511.3,504.4,497.9
XS GIS Cut Line= 3
     1912957.332      431656.562      1912806.29      431429.132
     1912641.359       431246.84
#Sta/Elev= 30
       0 1696.45    19.5 1692.63      39 1689.74    48.8 1687.81    58.5 1685.24
    68.2 1681.73      78 1677.82    97.5 1668.68   107.3  1664.6   126.8 1657.31
   146.3 1650.69     156 1648.62   165.8 1647.41   193.3 1644.86   204.8 1644.54
   214.5 1645.93   224.3 1648.51     234 1650.47   243.8 1650.84     273 1651.02
   351.7 1653.71   400.8 1654.55   410.7 1654.94   420.5 1655.77   430.4 1656.96
   440.2  1658.5   459.8 1662.99   469.7 1665.78   479.5 1668.87   518.8 1681.99
#Mann= 3 , 0 , 0
       0      .1       0   193.3    .045       0   214.5      .1       0
Bank Sta=193.3,214.5
XS Rating Curve= 0 ,0
Exp/Cntr=0.3,0.1

Type RM Length L Ch R = 1 ,18582.1 ,446,457,460.1
XS GIS Cut Line= 3
     1913397.479       431550.66     1913267.907        431252.7
     1912941.707       430956.91
#Sta/Elev= 30
       0 1677.67    19.1 1675.76    76.4 1668.93   143.3 1662.07   181.6  1656.7
   191.1 1655.14   200.7 1653.32   219.8 1649.13   229.4 1647.42   238.9 1646.62
   277.1 1647.47   286.7 1647.21   305.8 1645.53   324.9 1643.11   344.5 1641.14
   383.6 1639.75   432.6 1638.87   442.3 1638.69   452.1 1638.94   461.9 1640.51
   471.7 1642.29   481.5 1643.33   589.1  1642.7   657.6 1643.14   667.4 1644.18
   677.2  1647.6   696.8 1656.33   706.5 1660.34   716.3 1663.45   765.2 1674.42
#Mann= 3 , 0 , 0
       0      .1       0   432.6    .045       0   461.9      .1       0
Bank Sta=432.6,461.9
XS Rating Curve= 0 ,0
Exp/Cntr=0.3,0.1

Type RM Length L Ch R = 1 ,18125.1 ,414.7,400.5,365.5
XS GIS Cut Line= 4
     1913580.407       431105.13      1913467.56      430959.731
     1913326.501      430801.311     1913183.272      430699.314
#Sta/Elev= 30
       0 1683.22    38.8 1672.31    67.8 1663.67   106.6 1652.62   135.6 1643.78
   145.3 1641.45     155 1639.93   164.7 1639.25     184 1638.26   222.6 1636.66
   232.3 1635.99   241.9  1634.9   251.6 1634.45   260.9 1635.37   270.8 1637.22
   280.5 1637.66   290.1 1637.19   299.8 1636.48   309.4 1636.16     348 1636.18
   357.6 1636.48   376.9 1637.49   435.2 1641.37   474.3 1643.77   484.1 1645.04
   493.9 1647.08   513.4  1652.3   532.9 1658.01   542.7 1661.15     572 1671.35
#Mann= 3 , 0 , 0
       0     .07       0   241.9    .045       0   260.9     .08       0
Bank Sta=241.9,260.9
XS Rating Curve= 0 ,0
Exp/Cntr=0.3,0.1

Type RM Length L Ch R = 1 ,17724.7 ,380.4,399.6,388.3
XS GIS Cut Line= 4
     1913832.577       430790.46     1913691.952      430725.356
     1913557.838      430712.335     1913232.317      430591.241
#Sta/Elev= 30
       0 1677.23    19.4 1673.25    38.7 1669.76    77.5 1663.38   116.2 1657.55
     155 1650.81   164.6 1648.84   174.2 1644.88   183.8 1638.36   190.2 1635.09
   193.5 1633.41   203.1 1632.38   212.7 1632.85     232 1633.67   289.7 1635.12
     338 1635.59   386.2 1635.45   434.4 1636.14   453.7 1636.93     473 1638.06
   511.6 1640.91   521.2 1642.52   530.9 1645.32   540.6  1648.5   550.2 1650.92
   559.8 1652.85   569.5 1655.84   588.8 1663.12   598.4 1666.45     637 1679.28
#Mann= 3 , 0 , 0
       0      .1       0   190.2    .045       0   212.7      .1       0
Bank Sta=190.2,212.7
XS Rating Curve= 0 ,0
Exp/Cntr=0.3,0.1

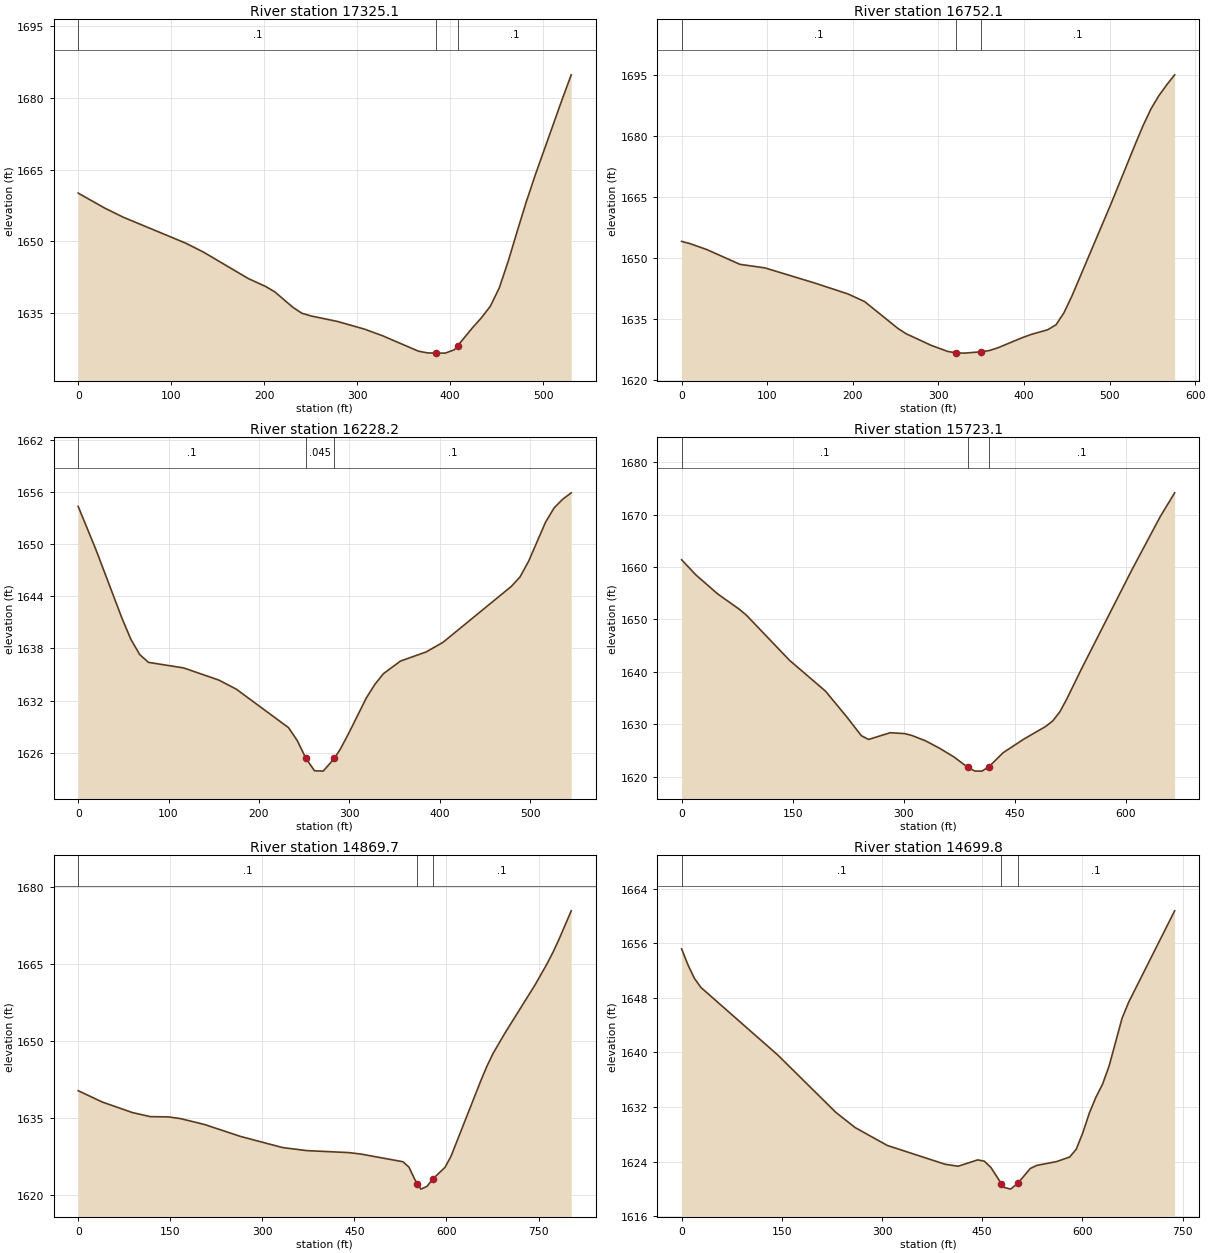
Type RM Length L Ch R = 1 ,17325.1 ,565.7,573,578.1
XS GIS Cut Line= 3
     1913827.123      430592.326     1913569.557      430462.335
     1913335.804      430401.354
#Sta/Elev= 30
       0 1660.07    28.8 1656.91    48.1 1655.06   115.4 1649.62   134.6 1647.74
   182.7 1642.22     202  1640.5   211.6 1639.38   230.8 1636.19   240.4 1634.95
     250 1634.39   278.9 1633.22   307.8 1631.62   327.2 1630.24   365.8 1627.01
   375.5 1626.65   385.1  1626.6   394.8 1626.61   404.5 1627.31   408.1 1628.15
   423.8 1631.88   433.5 1633.98   443.1  1636.4   452.8 1640.28   462.4 1645.86
   472.1 1652.14   481.8 1658.26   491.4 1663.85   520.4 1679.71   530.1 1684.81
#Mann= 3 , 0 , 0
       0      .1       0   385.1    .045       0   408.1      .1       0
Bank Sta=385.1,408.1
XS Rating Curve= 0 ,0
Exp/Cntr=0.3,0.1

Type RM Length L Ch R = 1 ,16752.1 ,535.1,523.9,509.7
XS GIS Cut Line= 3
      1913993.79       430215.59     1913644.832      429951.701
     1913509.415      429922.187
#Sta/Elev= 30
       0 1654.04     9.7  1653.5    29.2 1652.05    68.1 1648.39    97.2 1647.52
   155.6 1643.78   194.4 1641.09   213.9  1639.2   252.8 1632.59   262.5 1631.27
   291.7 1628.42   311.1 1626.92   320.8 1626.58   330.6 1626.51     350 1626.84
   359.7 1627.15   369.4 1627.81   398.6 1630.36   408.3  1631.1   427.8 1632.27
   437.5 1633.49   446.7 1636.43     456 1640.54   502.2 1663.53   529.9  1677.9
   539.1 1682.51   548.4 1686.66   557.6 1689.92   566.9 1692.63   576.1 1695.08
#Mann= 3 , 0 , 0
       0      .1       0   320.8    .045       0     350      .1       0
Bank Sta=320.8,350
XS Rating Curve= 0 ,0
Exp/Cntr=0.3,0.1

Type RM Length L Ch R = 1 ,16228.2 ,499,505.1,508.2
XS GIS Cut Line= 4
     1914085.804      429566.285     1913882.679      429545.451
     1913768.095      429548.924     1913552.818      429620.104
#Sta/Elev= 30
       0 1654.38    19.4 1649.46    48.6 1641.45    58.3 1639.06    68.1  1637.3
    77.8  1636.4   116.7 1635.76   155.6 1634.36     175 1633.31   232.8 1628.87
   242.4 1627.39     252 1625.33   261.5  1623.9   271.1 1623.86   283.5 1625.33
   290.2 1626.42   299.7 1628.29   318.8 1632.29   328.3 1633.86   337.7 1635.09
   356.6 1636.55     385  1637.6   403.8 1638.72   479.4 1645.17   488.9 1646.25
   498.3 1648.03   517.2 1652.57   526.7 1654.22   536.1 1655.21   545.6 1655.95
#Mann= 3 , 0 , 0
       0      .1       0     252    .045       0   283.5      .1       0
Bank Sta=252,283.5
XS Rating Curve= 0 ,0
Exp/Cntr=0.3,0.1

Type RM Length L Ch R = 1 ,15723.1 ,851.5,853.4,849.3
XS GIS Cut Line= 4
     1914186.498       429269.41     1913917.401      429133.993
     1913740.368      429097.292      1913556.29      429106.215
#Sta/Elev= 30
       0 1661.39    19.4 1658.49    48.6 1654.89    77.7 1651.98    87.5 1650.83
   145.8 1642.22   194.4 1636.34   223.5 1631.37   242.9 1627.84   252.7 1627.12
   281.8  1628.4   301.2 1628.24   310.8  1627.9   329.8 1626.85   348.8 1625.43
   367.9  1623.8   386.9 1621.79   396.4 1621.09   405.9 1621.08   415.4 1621.93
   434.5 1624.59     463 1627.23   491.8 1629.58   501.4 1630.63   511.2 1632.39
   520.8 1634.91   540.2 1640.52   608.1 1659.35   646.9 1669.63   666.3 1674.15
#Mann= 3 , 0 , 0
       0      .1       0   386.9    .045       0   415.4      .1       0
#XS Ineff= 2 , 0
          301.62 1628.21
Permanent Ineff=
       F       F
Bank Sta=386.9,415.4
XS Rating Curve= 0 ,0
Exp/Cntr=0.3,0.1

Type RM Length L Ch R = 1 ,14869.7 ,176.2,169.9,165
XS GIS Cut Line= 3
     1914389.623      428783.299     1913988.582      428469.062
     1913700.387      428411.771
#Sta/Elev= 30
       0 1640.36    39.2 1638.15    88.2  1636.1   117.6  1635.3     147 1635.25
   166.6 1634.92   205.8 1633.77   264.5 1631.44   333.1 1629.27   372.3 1628.68
   440.9 1628.29   460.5 1628.01   529.1 1626.51   538.9 1625.46   548.7 1622.98
  552.67 1622.19   558.5 1621.17   568.3 1621.71     578 1623.18   597.6 1625.41
   607.4 1627.57   656.4 1642.43   666.2  1645.2     676 1647.63   695.6 1651.65
   744.6 1661.03   764.1 1665.15   773.9 1667.42   783.7 1669.96   803.3 1675.42
#Mann= 3 , 0 , 0
       0      .1       0  552.67    .045       0     578      .1       0
Bank Sta=552.67,578
XS Rating Curve= 0 ,0
Exp/Cntr=0.3,0.1

Type RM Length L Ch R = 1 ,14699.8 ,173.3,173.9,173.1
XS GIS Cut Line= 3
     1914507.679      428357.951     1914104.901      428324.965
     1913773.304      428285.035
#Sta/Elev= 30
       0  1655.2     9.6 1652.84    19.2 1650.87    28.9 1649.54   144.3  1639.6
   230.9 1631.21   259.8 1628.98   307.9 1626.36   394.5  1623.6     414 1623.31
   443.4 1624.24   453.2 1624.05   463.1 1623.12  478.52 1620.77   482.7 1620.21
   492.5 1619.95   503.3  1620.8     522 1622.98   531.8 1623.43   561.3 1623.99
     581 1624.66   590.8  1625.8   600.6 1628.21   610.4 1631.11   620.2 1633.42
   630.1 1635.33   639.9 1637.99   659.5 1645.05   669.4  1647.4   738.1 1660.78
#Mann= 3 , 0 , 0
       0      .1       0  478.52    .045       0   503.3      .1       0
Bank Sta=478.52,503.3
XS Rating Curve= 0 ,0
Exp/Cntr=0.3,0.1

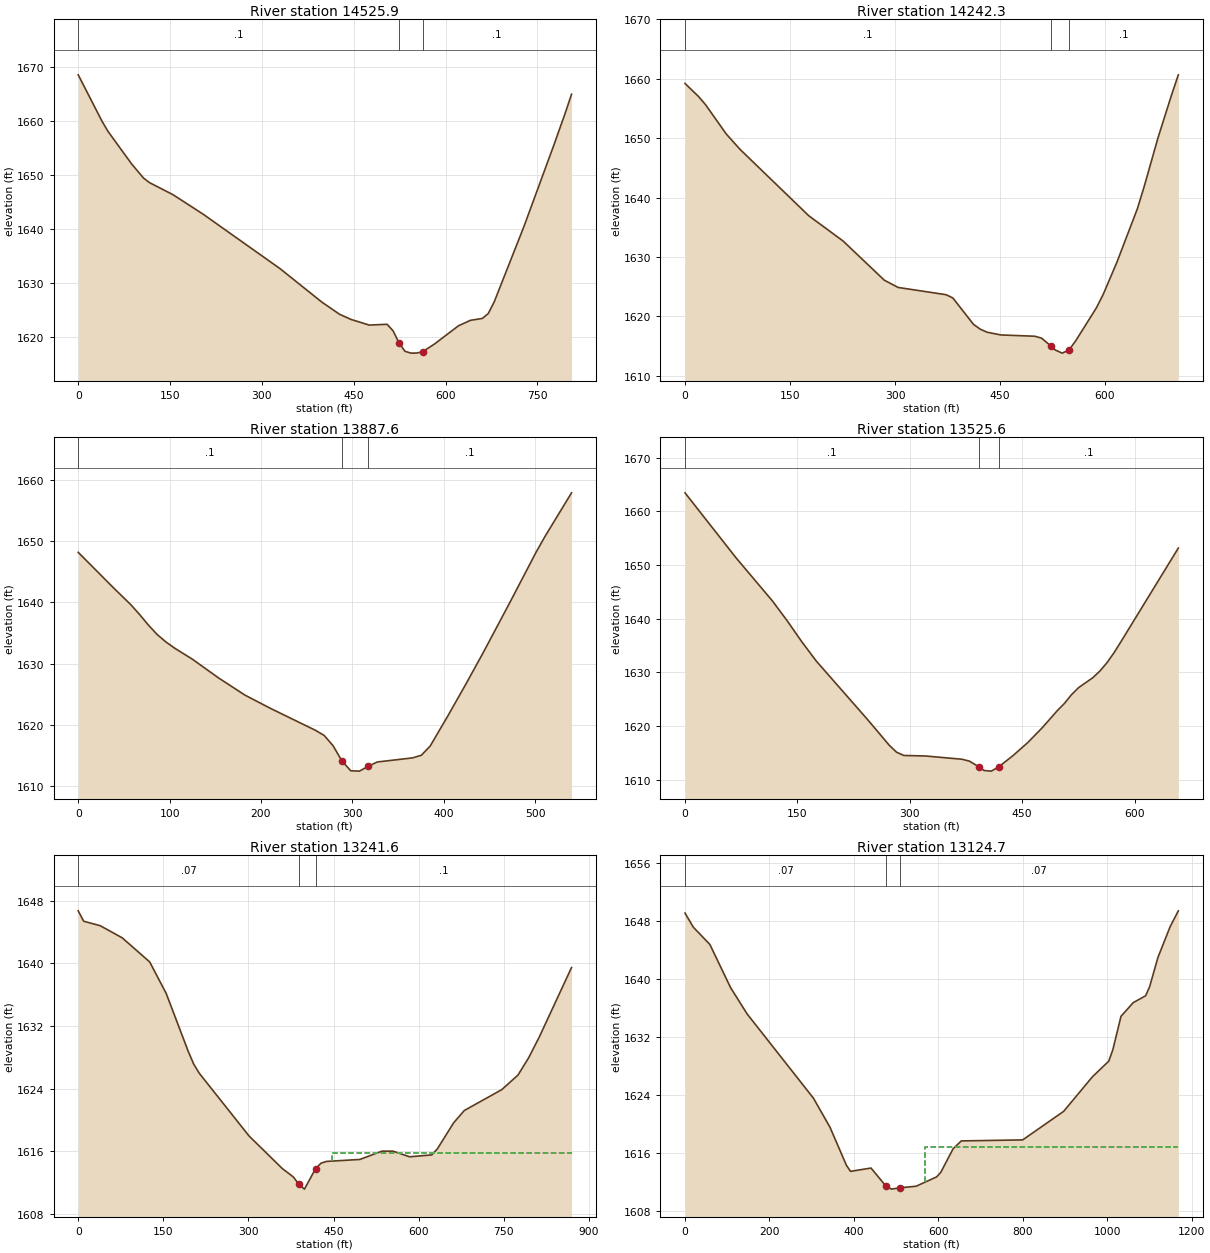
Type RM Length L Ch R = 1 ,14525.9 ,285.8,283.6,280.3
XS GIS Cut Line= 3
     1914563.234       428215.59     1914111.845      428151.354
     1913762.887      428173.924
#Sta/Elev= 30
       0 1668.47    38.8  1659.9    48.5 1658.03    87.3 1651.97   106.7 1649.36
   116.4 1648.52   155.2 1646.26   203.7  1642.7   329.8 1632.58   397.7 1626.42
   426.8 1624.15   446.2 1623.17   475.4 1622.15   504.5  1622.3   514.2 1621.08
   523.9 1618.87   533.6  1617.3   543.4 1616.96   553.1 1616.98   562.8 1617.24
   582.2 1618.68   621.1 1622.03   640.5 1623.03   659.9 1623.38   669.6 1624.28
   679.4 1626.46   727.9  1640.4   776.5 1655.39   795.9 1661.58   805.6 1664.88
#Mann= 3 , 0 , 0
       0      .1       0   523.9    .045       0   562.8      .1       0
Bank Sta=523.9,562.8
XS Rating Curve= 0 ,0
Exp/Cntr=0.3,0.1

Type RM Length L Ch R = 1 ,14242.3 ,354.9,354.7,353.4
XS GIS Cut Line= 3
     1914457.332       427894.41      1914118.79      427953.437
     1913762.887      428014.201
#Sta/Elev= 30
       0  1659.2    19.6 1656.97    29.5  1655.6    58.9  1650.7    78.6 1648.11
   176.7 1636.95   225.8 1632.69   284.7  1626.1   304.4 1624.88   372.9 1623.66
   382.7  1623.1     412 1618.68   421.7 1617.86   431.5 1617.35     451 1616.89
   499.8 1616.67   509.5 1616.34  522.43 1615.05     529 1614.35   538.8 1613.83
   548.6 1614.36   558.3 1615.94   587.6 1621.44   597.4 1623.72   616.9 1629.11
   646.2 1638.13   655.9 1641.85   675.4 1649.96   694.9 1657.23   704.7 1660.65
#Mann= 3 , 0 , 0
       0      .1       0  522.43    .045       0   548.6      .1       0
Bank Sta=522.43,548.6
XS Rating Curve= 0 ,0
Exp/Cntr=0.3,0.1

Type RM Length L Ch R = 1 ,13887.6 ,359.5,362,363.2
XS GIS Cut Line= 3
     1914257.245      427614.028     1914048.911       427648.75
     1913727.731      427718.194
#Sta/Elev= 30
       0 1648.15    38.4 1642.39    57.6  1639.6    67.2    1638    76.8 1636.28
    86.4 1634.74      96 1633.52   105.6  1632.5   124.8 1630.72   153.6 1627.65
   182.4 1624.85   211.2 1622.62   259.5 1619.11   269.2 1618.26   278.9 1616.58
   288.5 1614.12   298.2  1612.5   307.7 1612.44   317.5 1613.24   327.2 1613.93
   365.8  1614.6   375.5 1615.03   385.2 1616.55   404.5 1621.46   423.8 1626.54
   443.2 1631.79   472.2 1639.93   501.2 1648.22   510.8 1650.75   539.8 1657.86
#Mann= 3 , 0 , 0
       0      .1       0   288.5    .045       0   317.5      .1       0
Bank Sta=288.5,317.5
XS Rating Curve= 0 ,0
Exp/Cntr=0.3,0.1

Type RM Length L Ch R = 1 ,13525.6 ,299,284,276.6
XS GIS Cut Line= 3
     1914259.415      427311.076     1913755.943       427363.16
     1913613.582      427416.979
#Sta/Elev= 30
       0 1663.43    68.1 1651.32   116.8 1643.26   136.3  1639.6   155.7 1635.71
   175.2 1632.08   243.4 1621.22   272.6 1616.39   282.3  1615.1     292 1614.49
   321.2 1614.39   369.9 1613.78   379.6 1613.43  392.73 1612.33   399.1 1611.69
   408.8 1611.57   418.6 1612.36     438 1614.49   457.5  1616.9     477 1619.69
   496.4 1622.77   506.2 1624.16   515.7  1625.8   525.2 1627.12   544.2 1628.97
   553.7 1630.22   563.2 1631.78   572.7 1633.66   582.3  1635.8   658.4 1653.14
#Mann= 3 , 0 , 0
       0      .1       0  392.73    .045       0   418.6      .1       0
Bank Sta=392.73,418.6
XS Rating Curve= 0 ,0
Exp/Cntr=0.3,0.1

Type RM Length L Ch R = 1 ,13241.6 ,107.8,116.9,161.6
XS GIS Cut Line= 4
     1914289.609      426964.505     1914078.859      426997.361
     1913688.234      427175.312     1913495.338      427294.366
#Sta/Elev= 30
       0 1646.71     9.7 1645.38    38.8 1644.81    77.6 1643.26     126 1640.18
   155.1 1636.15   193.9 1628.76   203.6 1627.12   213.3 1625.97   301.1 1617.95
   359.6  1613.8   379.1 1612.72   388.9 1611.78   398.6 1611.17   418.2 1613.78
   427.9 1614.49   437.7 1614.71   496.2 1614.96   535.2 1616.02   554.7 1616.02
     584  1615.3     623 1615.54   632.8 1616.31   661.4 1619.63   680.3 1621.21
   746.4 1623.88   774.8 1625.73   793.7 1627.95   812.6 1630.63   869.2 1639.47
#Mann= 3 , 0 , 0
       0     .07       0   388.9    .045       0   418.2      .1       0
#XS Ineff= 2 , 0
                          447.86         1615.74
Permanent Ineff=
       F       F
Bank Sta=388.9,418.2
XS Rating Curve= 0 ,0
Exp/Cntr=0.3,0.1

Type RM Length L Ch R = 1 ,13124.7 ,352.5,420,391.9
XS GIS Cut Line= 4
     1914363.148       426821.58     1914042.213      426912.422
     1913712.352      427055.651     1913306.536      427303.047
#Sta/Elev= 30
       0 1649.09    19.6 1647.15    58.9 1644.76   107.9 1638.81   147.2 1635.17
   304.1 1623.56   343.3 1619.56   382.1 1614.32   391.9 1613.46   440.5 1613.92
  475.75 1611.44     489 1611.01   508.5 1611.19   547.4 1611.41     596  1612.7
   605.7 1613.32   634.8 1616.56   654.3 1617.66   799.8  1617.8   896.8 1621.74
   964.8  1626.5  1003.6 1628.66  1013.2 1630.23  1032.6 1634.85  1061.7 1636.74
  1090.8 1637.68  1100.5 1638.95  1119.9 1642.94    1149 1647.22  1168.4  1649.4
#Mann= 3 , 0 , 0
       0     .07       0  475.75    .045       0   508.5     .07       0
#XS Ineff= 2 , 0
                          567.54         1616.78
Permanent Ineff=
       F       F
Bank Sta=475.75,508.5
XS Rating Curve= 0 ,0
Exp/Cntr=0.3,0.1