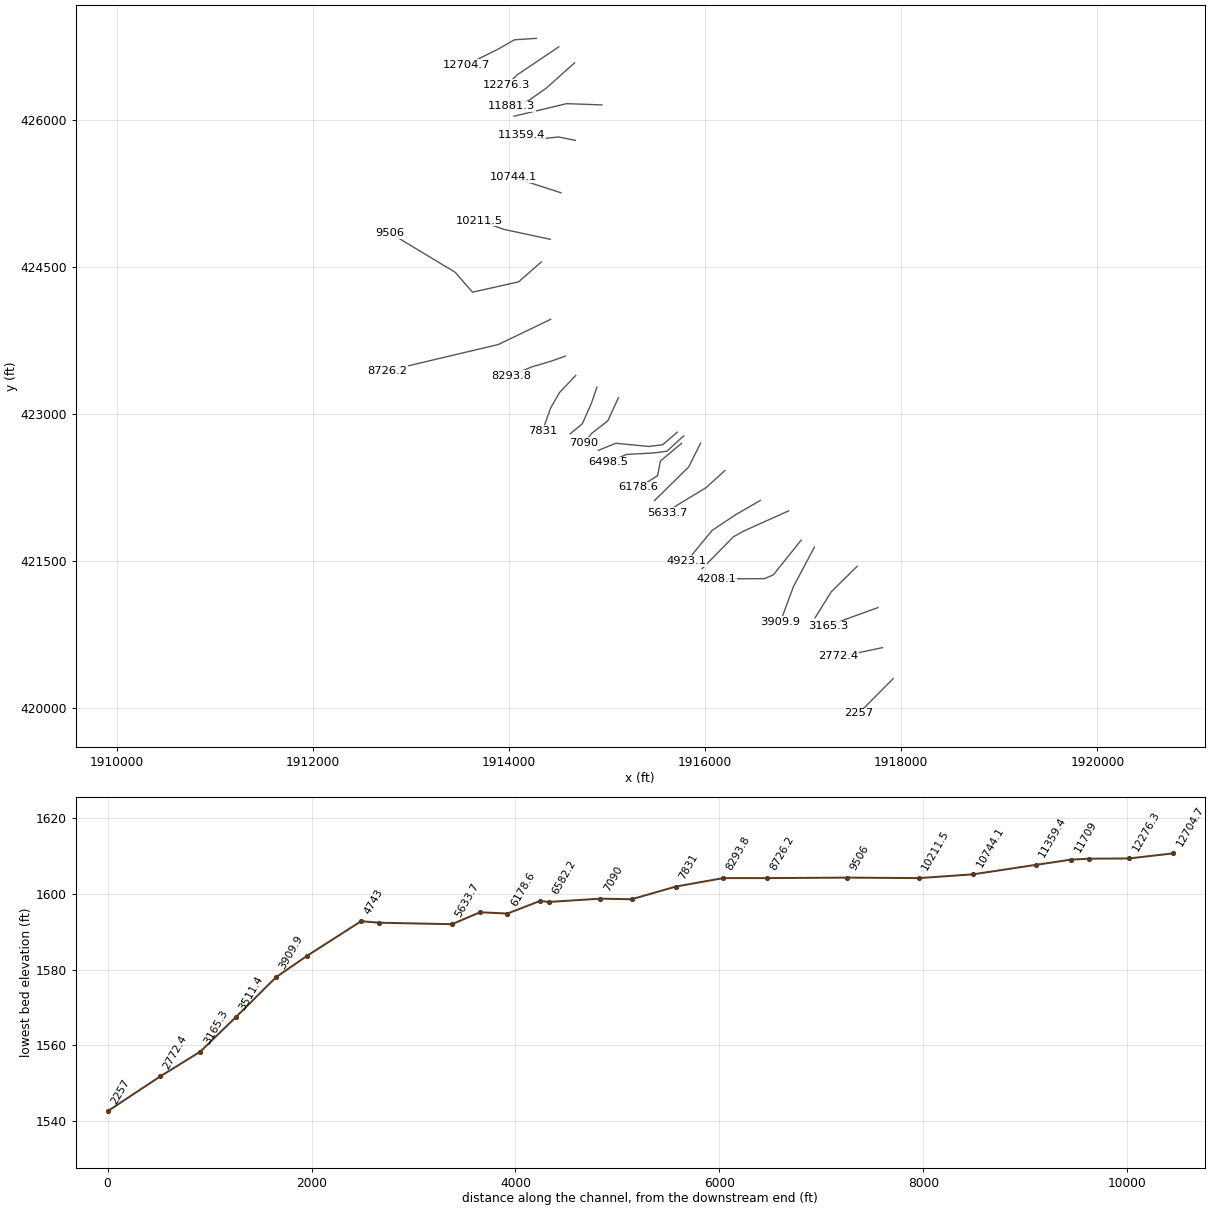
HEC-RAS study HAZELRUN.prj: HAZELRUN

--- HAZELRUN.g01 (geometry) --- (continued)

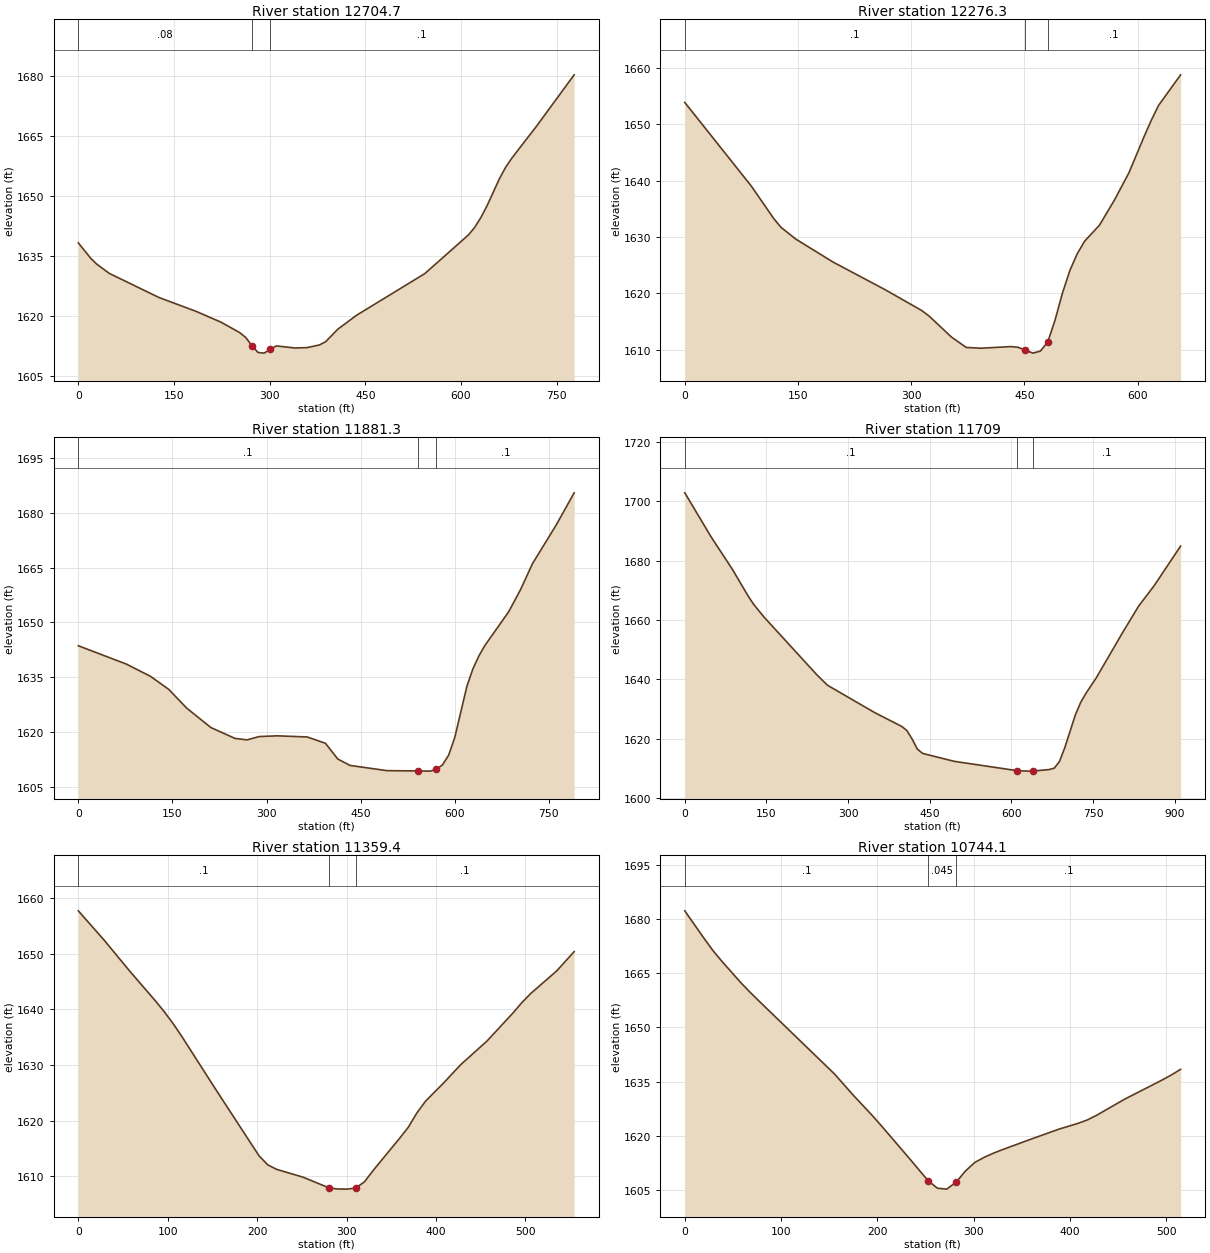
Type RM Length L Ch R = 1 ,12704.7 ,425.6,428.4,429.9
XS GIS Cut Line= 4
     1914276.588      426827.786     1914053.064      426812.595
     1913885.963      426717.109     1913562.612      426556.519
#Sta/Elev= 30
       0 1638.31    19.5 1634.45    29.2 1632.95    48.7 1630.67   126.6 1624.64
   185.1 1621.16     224 1618.46   252.9 1615.89   262.5 1614.66   272.2 1612.57
   281.8 1610.91   291.4 1610.74     301 1611.72   310.6 1612.54   339.5 1612.03
   358.8 1612.12     378 1612.78   387.6 1613.57   406.9 1616.72     436 1620.18
   543.4 1630.64   611.6 1640.28   621.4 1642.15   631.2 1644.64   640.9 1647.59
   660.4 1654.39   670.2 1657.25     680 1659.55     719  1667.6   777.5 1680.34
#Mann= 3 , 0 , 0
       0     .08       0   272.2    .045       0     301      .1       0
Bank Sta=272.2,301
XS Rating Curve= 0 ,0
Exp/Cntr=0.3,0.1

Type RM Length L Ch R = 1 ,12276.3 ,389.8,395,394.9
XS GIS Cut Line= 3
     1914506.377      426741.285     1914082.991      426456.314
     1913977.109      426354.696
#Sta/Elev= 30
       0 1653.88    88.3 1639.02   117.8  1633.3   127.6 1631.71   147.2 1629.63
   196.3 1625.58     265  1620.7   314.1 1616.96   323.9 1615.97   353.3 1612.27
     373 1610.42   392.6 1610.28   431.8 1610.57   441.6 1610.45   451.5 1609.94
   461.3 1609.41   471.1 1609.76   480.9 1611.33   490.7 1615.28   500.5 1620.06
   510.4  1624.1   520.1 1627.04   529.9 1629.27   549.5  1632.1   569.1 1636.49
   588.6  1641.4   608.2 1647.67     618 1650.65   627.8 1653.34   657.1 1658.78
#Mann= 3 , 0 , 0
       0      .1       0   451.5    .045       0   480.9      .1       0
Bank Sta=451.5,480.9
XS Rating Curve= 0 ,0
Exp/Cntr=0.3,0.1

Type RM Length L Ch R = 1 ,11881.3 ,185.4,172.4,163.2
XS GIS Cut Line= 4
     1914667.213       426578.22     1914380.755      426322.144
     1914196.293      426191.936     1914024.852      426135.512
#Sta/Elev= 30
       0 1643.62    76.8 1638.59   115.3 1635.23   144.1  1631.7   172.9 1626.55
   211.3 1621.26   249.8 1618.28     269 1617.88   288.2 1618.79     317 1618.99
     365 1618.68     394 1616.95   413.7 1612.64   433.3 1610.89   492.2 1609.47
   541.3 1609.39   560.9 1609.34   570.8 1609.82   580.6 1611.06   590.4  1613.7
   600.2 1618.56   619.5 1632.54     629 1637.26   638.5  1640.8     648 1643.65
     686 1652.88     705 1658.95     724 1666.04     762 1676.67   790.5 1685.43
#Mann= 3 , 0 , 0
       0      .1       0   541.3    .045       0   570.8      .1       0
Bank Sta=541.3,570.8
XS Rating Curve= 0 ,0
Exp/Cntr=0.3,0.1

Type RM Length L Ch R = 1 ,11709   ,355.4,349.6,343.6
XS GIS Cut Line= 3
     1914945.678       426149.01     1914586.303      426162.031
     1914049.845      426034.427
#Sta/Elev= 30
       0 1702.85    48.6 1687.93    87.5 1677.06   116.6 1668.03   126.4 1665.31
   145.8 1660.95     243 1641.48   262.4    1638   349.9 1628.71   398.3 1624.19
     408  1622.8   417.7  1619.9   427.3 1616.52     437 1615.06     495  1612.4
   611.1 1609.24   630.5  1609.1   640.2 1609.15   669.2 1609.62   678.9 1610.11
   688.5 1612.38   698.2 1617.02   717.6 1628.04   727.2 1632.18   736.9 1635.26
   756.2 1640.58   804.6 1655.83   833.6 1664.61   862.7 1671.65     911 1684.92
#Mann= 3 , 0 , 0
       0      .1       0   611.1    .045       0   640.2      .1       0
Bank Sta=611.1,640.2
XS Rating Curve= 0 ,0
Exp/Cntr=0.3,0.1

Type RM Length L Ch R = 1 ,11359.4 ,620.8,615.3,604.4
XS GIS Cut Line= 4
     1914675.025      425787.422     1914505.755      425822.144
     1914310.442      425802.613      1914128.15      425837.335
#Sta/Elev= 30
       0  1657.7    28.8 1652.45    57.6 1646.85    86.4 1641.49      96  1639.6
   105.6 1637.53   115.2 1635.27   153.6 1625.64   202.2 1613.67     212 1612.05
   221.9 1611.25   251.3 1609.85   280.8  1607.9   290.6 1607.72   300.4  1607.7
   310.2 1607.89     320    1609   329.8 1611.06   359.3 1616.82   369.1 1618.82
   378.8 1621.42   388.6 1623.54   408.2 1626.71   427.7 1630.06     457 1634.29
   486.3 1639.37     496 1641.19   505.8 1642.81   535.1 1646.91   554.6 1650.37
#Mann= 3 , 0 , 0
       0      .1       0   280.8    .045       0   310.2      .1       0
Bank Sta=280.8,310.2
XS Rating Curve= 0 ,0
Exp/Cntr=0.3,0.1

Type RM Length L Ch R = 1 ,10744.1 ,530.1,532.6,534.9
XS GIS Cut Line= 2
     1914528.143      425253.177      1914038.56      425412.031
#Sta/Elev= 30
       0 1682.27    19.4 1674.87    29.1 1671.31    38.8  1668.2    58.3 1662.34
      68 1659.66    77.7 1657.12   155.4 1637.09   174.8 1631.24   194.2 1625.71
   203.9  1622.8   233.1 1613.71   252.5 1607.55   262.2 1605.46   271.9  1605.2
   281.6 1607.12   291.4 1610.23   301.1 1612.61   310.8    1614   320.5 1615.17
   330.2 1616.18   359.3 1619.03   388.5 1621.82   407.9 1623.39   417.6 1624.33
   427.3 1625.62   456.4 1630.08   495.3 1635.39     505 1636.81   514.7 1638.37
#Mann= 3 , 0 , 0
       0      .1       0   252.5    .045       0   281.6      .1       0
Bank Sta=252.5,281.6
XS Rating Curve= 0 ,0
Exp/Cntr=0.3,0.1

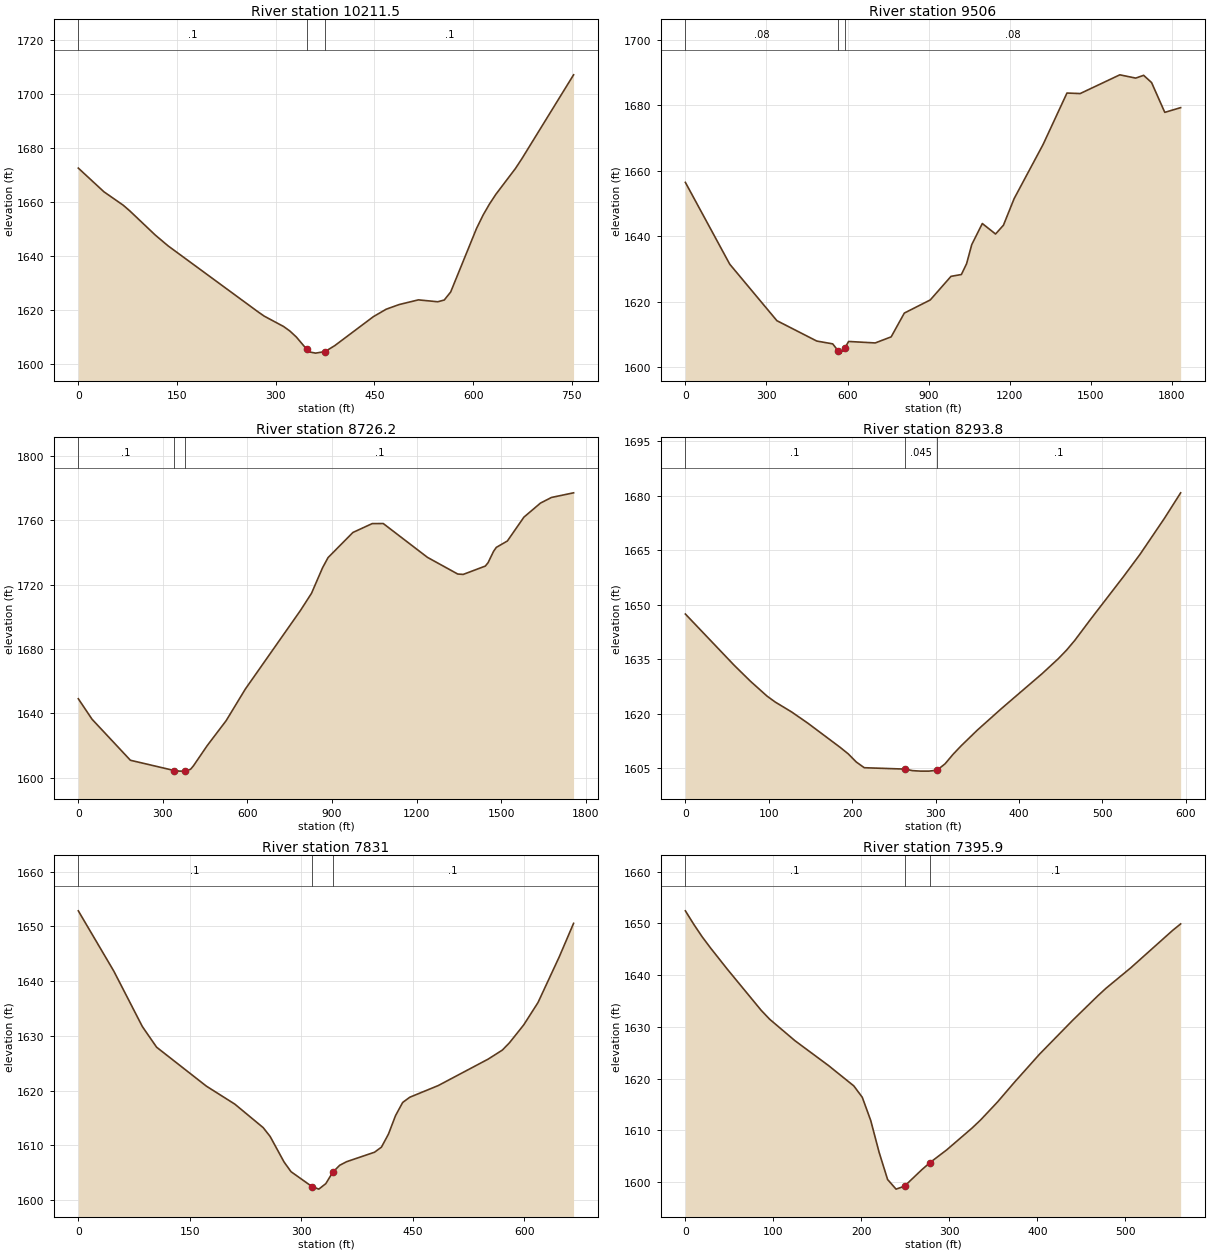
Type RM Length L Ch R = 1 ,10211.5 ,695.2,705.5,714
XS GIS Cut Line= 3
     1914419.636      424779.219     1913943.074      424880.781
     1913693.074      424969.323
#Sta/Elev= 30
       0 1672.71      39 1663.93    68.2 1658.98      78 1656.92   116.9 1647.93
   136.4 1643.92   272.9 1619.52   282.6 1617.88   311.8 1614.08   321.6 1612.36
   331.3 1610.16  347.03 1605.64   350.8 1604.66   360.6  1604.2  375.13  1604.8
   389.8    1607   448.3  1617.7   467.8 1620.46   487.3 1622.17   516.7 1623.92
   546.2 1623.22     556 1623.86   565.8 1626.85   605.1 1650.39     615  1655.3
   624.8 1659.44   634.6 1663.06   664.1 1672.54   673.9 1676.17   752.5 1707.25
#Mann= 3 , 0 , 0
       0      .1       0  347.03    .045       0  375.13      .1       0
Bank Sta=347.03,375.13
XS Rating Curve= 0 ,0
Exp/Cntr=0.3,0.1

Type RM Length L Ch R = 1 ,9506    ,773.1,779.8,741
XS GIS Cut Line= 5
     1914328.056      424549.184     1914095.852      424345.191
     1913625.546      424240.113      1913449.15      424442.847
     1912787.005      424841.675
#Sta/Elev= 30
       0 1656.46   164.2 1631.48   338.6 1614.24   486.1 1608.02   545.1 1607.16
   564.8 1605.09   574.6 1604.33  590.08 1605.94   604.1 1607.89   702.5 1607.44
   761.5  1609.3   810.2 1616.56   906.2 1620.57   982.9 1627.77  1021.3 1628.33
  1040.5 1631.61  1059.7 1637.46  1098.8  1643.9  1147.8  1640.7  1177.1  1643.4
  1216.3 1651.47  1323.9 1668.07    1412 1683.74  1460.9 1683.58  1607.6  1689.3
  1666.4  1688.3  1695.7 1689.15  1725.1 1686.94    1774 1677.84  1832.7 1679.28
#Mann= 3 , 0 , 0
       0     .08       0   564.8    .045       0  590.08     .08       0
Bank Sta=564.8,590.08
XS Rating Curve= 0 ,0
Exp/Cntr=0.3,0.1

Type RM Length L Ch R = 1 ,8726.2  ,429.8,432.3,426.7
XS GIS Cut Line= 4
     1914423.289      423964.071     1914344.549      423925.486
     1913889.688      423706.736     1912756.623      423438.898
#Sta/Elev= 30
       0 1649.13    48.7 1636.42   184.8 1610.94     340 1604.58   359.5  1604.2
   378.9 1604.21   398.3 1605.37     408 1607.39   456.5 1619.86   524.5 1635.54
   592.4 1655.12   788.1 1703.95   827.2 1714.57   866.4 1730.43   885.9 1736.73
     974 1752.32  1042.5 1757.83  1081.6 1757.87  1238.2  1736.9  1345.8 1726.52
  1365.4 1726.29  1443.6 1731.46  1453.4 1733.55    1473 1740.64  1482.8 1743.08
  1521.9 1747.03  1580.6 1761.83  1639.3 1770.55  1678.4 1774.05  1756.7 1776.92
#Mann= 3 , 0 , 0
       0      .1       0     340    .045       0   378.9      .1       0
Bank Sta=340,378.9
XS Rating Curve= 0 ,0
Exp/Cntr=0.3,0.1

Type RM Length L Ch R = 1 ,8293.8  ,445.9,462.8,478.9
XS GIS Cut Line= 4
     1914574.476      423588.637     1914426.906      423536.554
     1914222.913       423475.79      1914016.75      423386.814
#Sta/Elev= 30
       0 1647.45    58.7  1633.3    78.2 1628.91    97.8 1624.88   107.6 1623.24
   127.2 1620.52   146.7 1617.43   185.5 1610.76   195.2 1608.97   204.9 1606.72
   214.5 1605.14   262.9 1604.76   272.6 1604.33   282.3  1604.2   291.9  1604.2
   301.6 1604.44   311.3 1606.19     321 1608.83   330.6 1611.15     350 1615.47
   379.1 1621.44   427.9 1631.06   447.4  1635.2   457.2 1637.54     467 1640.21
   486.5 1646.18   525.6 1657.83   545.1 1663.86   574.4 1673.78   593.9 1680.82
#Mann= 3 , 0 , 0
       0      .1       0   262.9    .045       0   301.6      .1       0
Bank Sta=262.9,301.6
XS Rating Curve= 0 ,0
Exp/Cntr=0.3,0.1

Type RM Length L Ch R = 1 ,7831    ,432.5,435.1,435.4
XS GIS Cut Line= 4
     1914678.642      423391.154     1914513.712      423217.543
     1914424.736      423063.463     1914340.101      422829.088
#Sta/Elev= 30
       0 1652.86    47.9 1641.81    86.2  1631.7   105.4 1627.92   172.4  1620.8
   210.7 1617.51   248.8 1613.22   258.2  1611.6   276.9 1606.94   286.3 1605.16
   314.4 1602.45   323.7 1601.97   333.1 1602.97   342.5 1605.06   351.8 1606.33
   361.2 1606.99   398.7 1608.72     408 1609.65   417.4 1612.02     427 1615.42
   436.6 1617.82   446.1 1618.77   484.5 1620.91   551.6 1625.74   570.7 1627.39
   580.3 1628.73   599.5    1632   618.7 1636.08   647.4 1644.47   666.6 1650.57
#Mann= 3 , 0 , 0
       0      .1       0   314.4    .045       0   342.5      .1       0
Bank Sta=314.4,342.5
XS Rating Curve= 0 ,0
Exp/Cntr=0.3,0.1

Type RM Length L Ch R = 1 ,7395.9  ,318.2,305.9,295.7
XS GIS Cut Line= 4
     1914895.656      423271.797     1914839.233      423109.036
     1914745.917      422898.533     1914622.219      422796.536
#Sta/Elev= 30
       0 1652.44     9.6 1649.81    19.1 1647.41    28.7 1645.23    47.8 1641.12
    86.1  1633.2    95.7 1631.48   124.4 1627.33   162.7  1622.5   191.4 1618.57
     201 1616.37   210.6 1611.89   220.2 1605.69   229.8 1600.46   239.4  1598.6
     249 1599.17   268.2 1602.28   277.8 1603.71     297  1606.2   325.8 1610.42
   335.4 1611.97   354.6 1615.44   373.7 1619.23   402.5 1624.72   440.2 1631.28
   468.5 1635.97     478 1637.46   506.3 1641.44   553.4 1648.61   562.8 1649.91
#Mann= 3 , 0 , 0
       0      .1       0     249    .045       0   277.8      .1       0
Bank Sta=249,277.8
XS Rating Curve= 0 ,0
Exp/Cntr=0.3,0.1

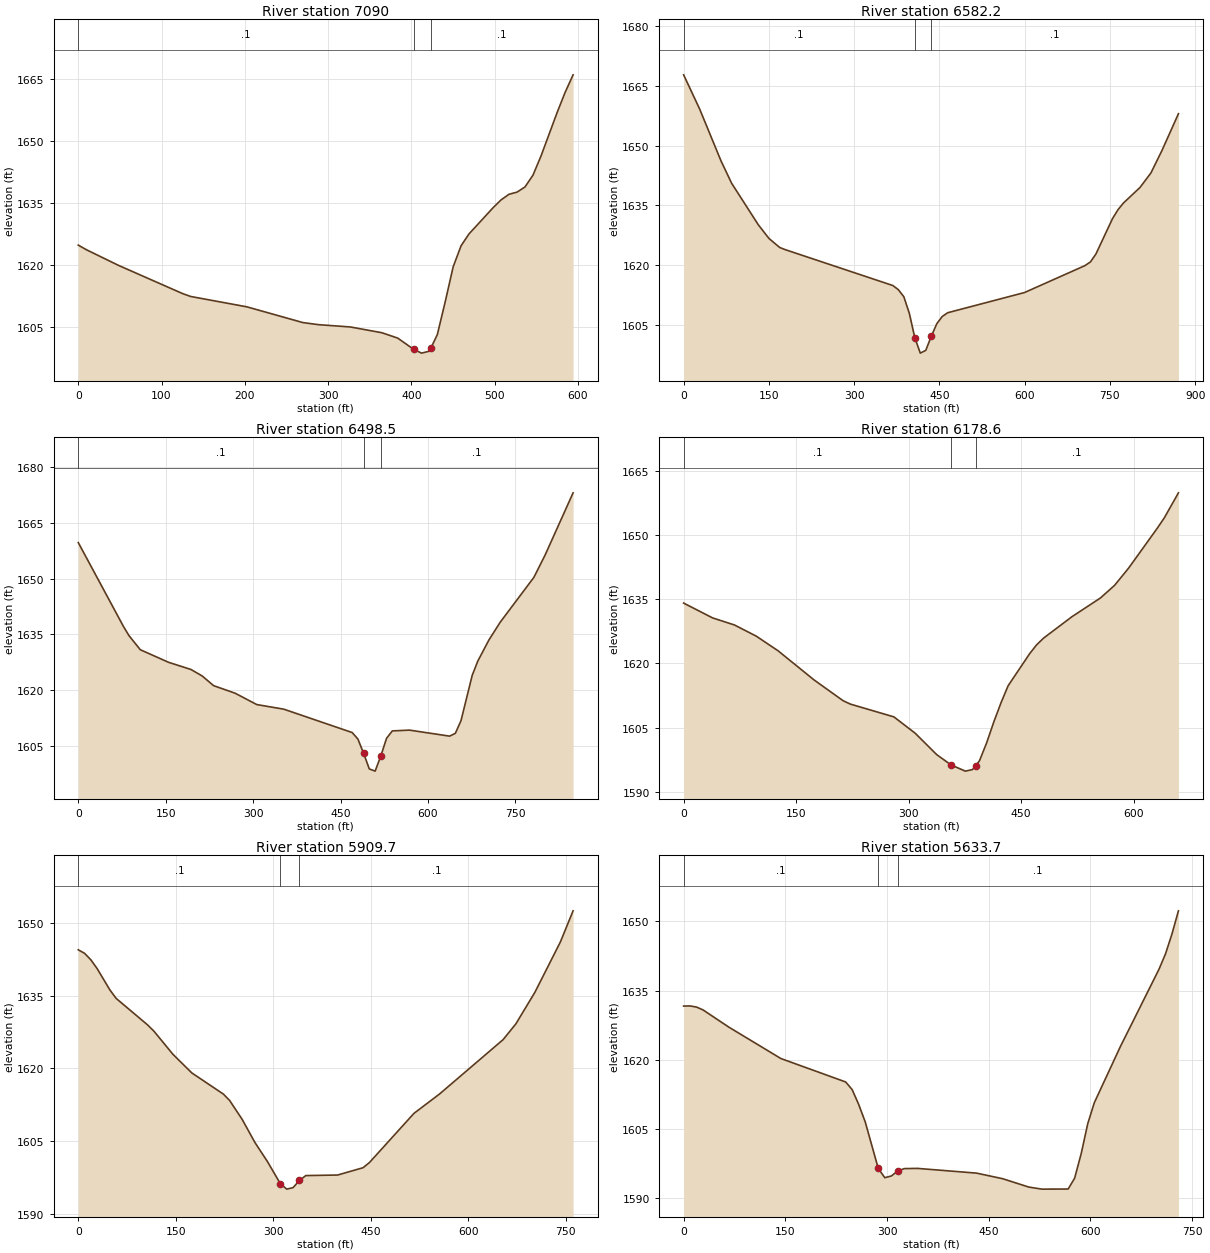
Type RM Length L Ch R = 1 ,7090    ,524.7,507.8,484.6
XS GIS Cut Line= 4
      1915114.84       423165.46     1915006.333      422928.915
     1914841.403      422800.877     1914763.278       422703.22
#Sta/Elev= 30
       0  1624.9     9.6 1623.79    48.2    1620   125.3 1613.16   134.9 1612.47
   202.4 1609.96   269.7 1606.15   288.7 1605.64   326.7 1605.09   364.6 1603.69
   383.6 1602.39   402.6 1599.69   412.1 1598.76   421.6 1599.23   423.7 1600.12
   431.1 1603.25   440.6 1611.21   450.1 1619.63   459.6 1624.73     469 1627.57
   497.9 1633.91   507.5 1635.81   517.1 1637.19   526.8 1637.71   536.4 1638.97
     546 1641.84   555.6 1646.46   574.9 1656.95   584.5 1661.83   594.1 1666.09
#Mann= 3 , 0 , 0
       0      .1       0   402.6    .045       0   423.7      .1       0
Bank Sta=402.6,423.7
XS Rating Curve= 0 ,0
Exp/Cntr=0.3,0.1

Type RM Length L Ch R = 1 ,6582.2  ,79.4,83.7,93.4
XS GIS Cut Line= 5
     1915715.209      422812.784      1915565.47      422684.745
     1915424.411      422667.384     1915088.039      422699.936
     1914908.677      422627.266
#Sta/Elev= 30
       0 1667.79    28.2  1659.2    65.7  1646.2    84.4 1640.57   131.3 1630.15
   150.1  1626.7   168.9 1624.44   178.2 1623.91   368.1 1614.87   377.8 1613.82
   387.4 1612.06   397.1  1607.9   406.7  1601.8   416.4 1597.89     426 1598.58
   435.7  1602.1   445.4 1605.27     455 1607.09   464.7 1608.04   599.8 1613.11
   706.1 1619.87   715.8  1620.8   725.5 1622.81   754.5 1631.65   764.2  1633.9
   773.8 1635.59   802.9 1639.49   822.2 1643.15   841.6 1648.78   870.6 1658.02
#Mann= 3 , 0 , 0
       0      .1       0   406.7    .045       0   435.7      .1       0
Bank Sta=406.7,435.7
XS Rating Curve= 0 ,0
Exp/Cntr=0.3,0.1

Type RM Length L Ch R = 1 ,6498.5  ,289.8,319.9,349.7
XS GIS Cut Line= 5
     1915780.313      422775.891     1915609.198      422619.019
     1915480.726      422601.658     1915196.003      422586.033
     1915010.674      422505.738
#Sta/Elev= 30
       0 1659.75    77.4 1637.18      87 1634.67   106.4 1630.88   154.8 1627.49
   193.4 1625.55   212.8 1623.78   232.1  1621.2   269.2 1619.15   306.2  1616.1
   352.5 1614.86   469.9 1608.56   479.8 1606.79   489.6 1602.92   499.3 1598.75
   509.3 1598.16   519.1 1602.28   528.9 1607.02   538.8    1609   568.3 1609.21
   637.1 1607.59   646.9 1608.35   656.6 1611.76   675.8 1623.96   685.4 1627.81
   704.6 1633.53   723.9  1638.3   781.6 1650.37   800.8 1656.36   848.9 1673.16
#Mann= 3 , 0 , 0
       0      .1       0   489.6    .045       0   519.1      .1       0
Bank Sta=489.6,519.1
XS Rating Curve= 0 ,0
Exp/Cntr=0.3,0.1

Type RM Length L Ch R = 1 ,6178.6  ,283.1,269,252.2
XS GIS Cut Line= 4
     1915757.201       422698.88     1915542.358      422518.759
     1915514.146      422369.019     1915321.003      422249.661
#Sta/Elev= 30
       0 1634.07    38.7  1630.6    67.7 1628.96    96.7 1626.36   125.7 1622.96
     174 1616.11   212.7 1611.26   222.4 1610.47   280.4 1607.49   308.9 1603.65
   337.5 1598.67   356.6 1596.27   375.6 1594.82   385.1 1595.18  389.39 1596.04
   394.6 1597.28   404.2  1601.5   413.7 1606.36   423.2 1610.78   432.7 1614.76
   461.1 1622.18   470.6  1624.3     480 1625.89   517.9  1630.9   555.7 1635.25
   574.6  1638.2   593.6 1642.29   631.4 1651.51   640.9 1653.96   659.8 1659.82
#Mann= 3 , 0 , 0
       0      .1       0   356.6    .045       0  389.39      .1       0
Bank Sta=356.6,389.39
XS Rating Curve= 0 ,0
Exp/Cntr=0.3,0.1

Type RM Length L Ch R = 1 ,5909.7  ,281,276,272.5
XS GIS Cut Line= 3
     1915952.514       422701.05     1915830.986      422457.995
     1915481.594      422115.113
#Sta/Elev= 30
       0 1644.43     9.7  1643.7    19.4 1642.36    29.1 1640.54    48.5  1636.2
    58.2 1634.43   106.8 1628.95   116.5 1627.66   145.6 1622.92   174.7 1619.08
   223.2 1614.73   232.9 1613.41   252.3 1609.49   271.7 1604.78   291.3 1600.78
   310.9 1596.28   320.7 1595.16   330.5 1595.47   340.3 1596.95   350.1 1597.95
     399 1598.06   438.2 1599.57     448 1600.64   516.5 1610.76   555.7 1614.73
   653.6 1625.93   673.2 1629.17   702.5 1635.67   741.7 1646.03   761.3 1652.45
#Mann= 3 , 0 , 0
       0      .1       0   310.9    .045       0   340.3      .1       0
Bank Sta=310.9,340.3
XS Rating Curve= 0 ,0
Exp/Cntr=0.3,0.1

Type RM Length L Ch R = 1 ,5633.7  ,668.5,710.6,710.1
XS GIS Cut Line= 4
      1916199.91      422421.102     1916008.937      422247.491
     1915711.628       422067.37     1915611.802      421993.585
#Sta/Elev= 30
       0 1631.65     9.6 1631.68    19.1 1631.43    28.7 1630.81    66.9 1627.07
   143.4 1620.29     239 1615.21   248.5 1613.57   258.1 1610.38   267.8 1606.58
   287.1 1596.47   296.7 1594.48   306.4 1594.85     316 1595.95   325.7 1596.45
     345 1596.49   431.9 1595.47   470.5 1594.26   509.2 1592.44   528.5    1592
   567.1 1592.02   576.7 1594.37   586.4 1599.71     596 1606.15   605.7 1610.71
   643.9  1622.8   701.2 1639.65   710.7 1642.95   720.3 1647.29   729.8 1652.28
#Mann= 3 , 0 , 0
       0      .1       0   287.1    .045       0     316      .1       0
Bank Sta=287.1,316
XS Rating Curve= 0 ,0
Exp/Cntr=0.3,0.1

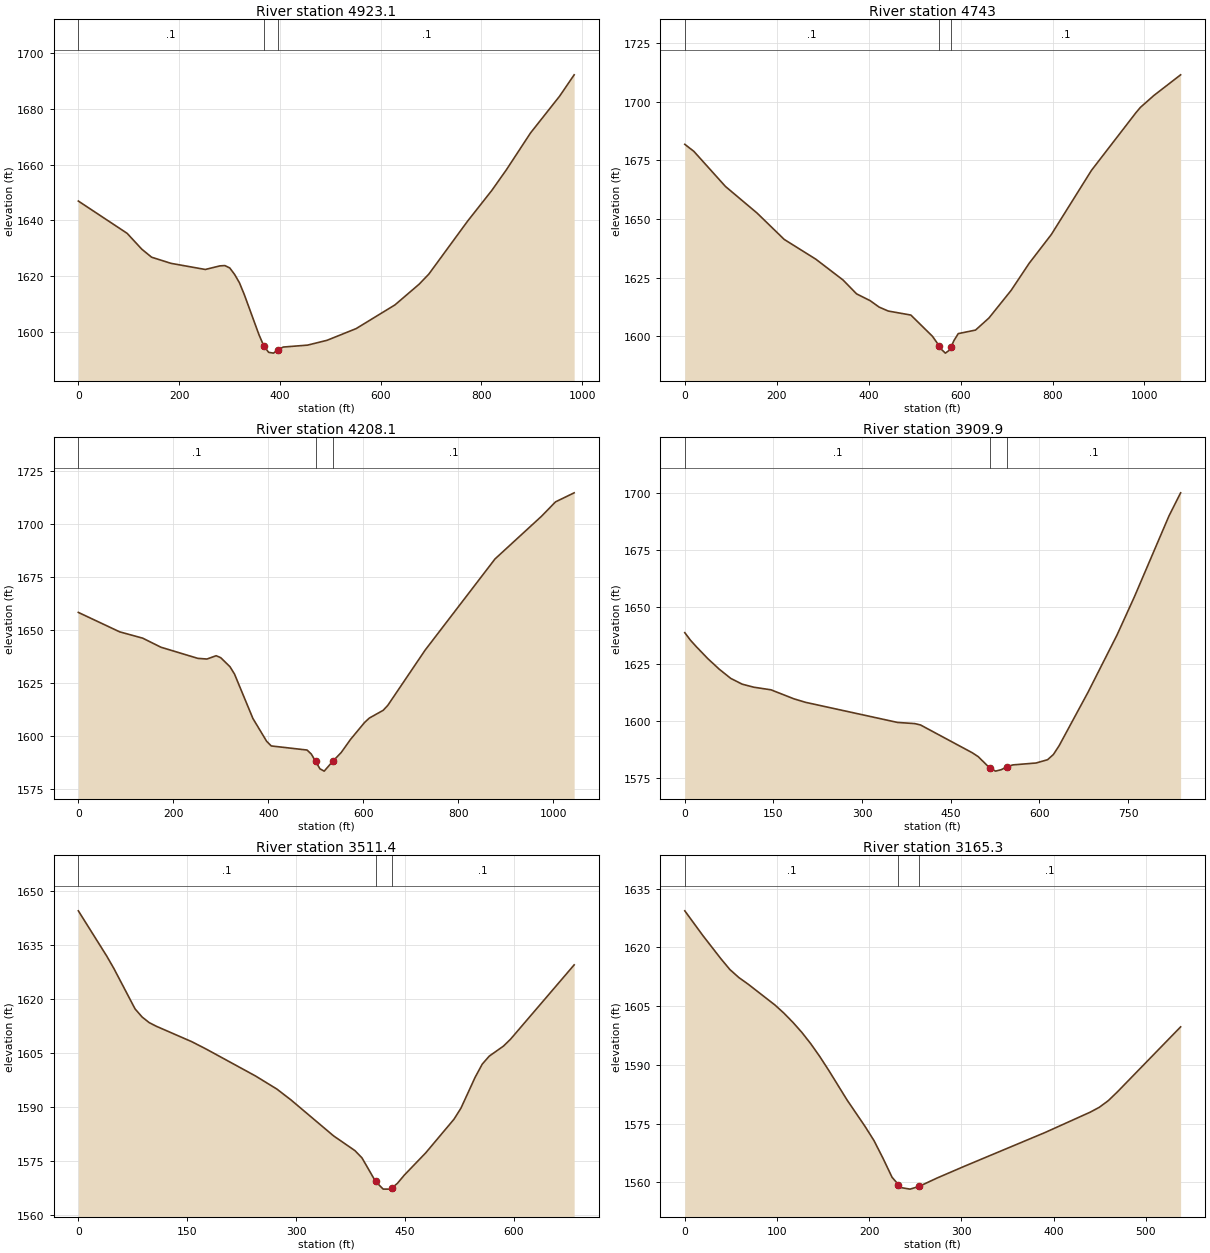
Type RM Length L Ch R = 1 ,4923.1  ,181.5,180.1,182.4
XS GIS Cut Line= 4
     1916562.323      422117.283     1916310.587      421971.884
     1916069.701      421811.293     1915812.865      421499.849
#Sta/Elev= 30
       0 1646.95    96.9 1635.36     126 1629.67   145.4  1626.8   184.1 1624.59
     252  1622.4     281 1623.69   290.7  1623.8   300.4 1622.96     310 1620.66
   319.7 1617.64   329.3 1613.41   358.3 1599.08   367.9 1595.02   377.6 1592.68
   387.2 1592.39   396.9 1593.66   406.5 1594.57   454.8 1595.26   493.4 1596.98
   551.3 1601.19   628.3 1609.69   676.3 1617.12   695.6 1620.76   772.4 1639.73
   820.5 1650.76   849.3 1658.13   897.4  1671.4   955.1 1684.59   983.9 1692.23
#Mann= 3 , 0 , 0
       0      .1       0   367.9    .045       0   396.9      .1       0
Bank Sta=367.9,396.9
XS Rating Curve= 0 ,0
Exp/Cntr=0.3,0.1

Type RM Length L Ch R = 1 ,4743    ,537.4,534.9,532.3
XS GIS Cut Line= 4
     1916850.626        422010.7     1916393.052      421805.217
     1916287.149      421746.189     1915967.813      421420.856
#Sta/Elev= 30
       0 1681.85    19.7 1678.86    88.5 1663.87   157.4  1652.5   216.4 1641.27
   285.2 1632.84   344.2 1623.99   373.7 1618.07   403.2 1615.17   422.9 1612.41
   442.6 1610.74   491.8 1609.03   538.9 1599.95  553.68 1595.81   557.6 1594.52
   566.9 1592.79   576.2 1594.12     579 1595.32   585.5 1598.12   594.9 1601.11
   632.5 1602.62   661.6 1607.75   710.1 1619.59   748.9 1631.02   797.4 1643.38
   884.7 1670.73   981.7  1695.4   991.4 1697.64  1020.5 1702.68  1078.7 1711.49
#Mann= 3 , 0 , 0
       0      .1       0  553.68    .045       0     579      .1       0
Bank Sta=553.68,579
XS Rating Curve= 0 ,0
Exp/Cntr=0.3,0.1

Type RM Length L Ch R = 1 ,4208.1  ,279.6,298.2,316.8
XS GIS Cut Line= 4
      1916978.23      421712.523     1916694.267      421357.734
     1916602.796      421319.728      1916112.67      421317.804
#Sta/Elev= 30
       0 1658.43      87 1649.26   135.4 1646.28     174 1641.99   251.4 1636.75
   270.7 1636.43   290.1 1637.99   299.7 1637.07   319.1 1632.82   328.7 1629.35
   367.4 1608.41   396.4  1597.6   406.1 1595.42   481.4 1593.49   490.4 1591.58
   499.5 1588.12   508.5 1584.63   517.5 1583.54   535.5 1588.16   553.5 1592.38
   573.1 1598.56   602.5  1606.5   612.3 1608.55   641.7 1612.24   651.5 1614.61
   729.9 1640.62     877 1683.65     975 1703.82  1004.4 1710.59  1043.6 1714.85
#Mann= 3 , 0 , 0
       0      .1       0   499.5    .045       0   535.5      .1       0
Bank Sta=499.5,535.5
XS Rating Curve= 0 ,0
Exp/Cntr=0.3,0.1

Type RM Length L Ch R = 1 ,3909.9  ,403.1,398.5,393.6
XS GIS Cut Line= 3
     1917113.972      421641.343     1916899.128      421237.697
      1916766.75      420879.624
#Sta/Elev= 30
       0  1638.7     9.7 1635.36    19.5 1632.56    38.9 1627.33    58.4 1622.66
    77.8 1618.64    97.3  1616.1   116.8 1614.79   145.9 1613.64   184.8 1609.68
   204.3 1608.16     360 1599.34   389.2 1598.83   398.9 1598.23   486.6 1586.02
   496.4 1584.36     516 1579.38   525.8 1577.99   535.6 1578.63   545.4 1579.94
   555.2 1580.72   594.3 1581.55   613.9    1583   623.7 1585.28   633.5 1589.18
   682.4 1612.63   731.3 1637.64   760.7 1654.38   819.4 1689.95     839 1700.02
#Mann= 3 , 0 , 0
       0      .1       0     516    .045       0   545.4      .1       0
Bank Sta=516,545.4
XS Rating Curve= 0 ,0
Exp/Cntr=0.3,0.1

Type RM Length L Ch R = 1 ,3511.4  ,360.9,346.1,330.8
XS GIS Cut Line= 3
      1917550.17       421446.03     1917285.413      421185.613
     1917120.483      420920.856
#Sta/Elev= 30
       0 1644.61    39.1 1632.06    48.9 1628.63    78.2 1617.37      88  1615.1
    97.7 1613.56   107.5 1612.55   156.4 1608.26   175.9 1606.25   244.3 1598.73
   273.6 1595.11   293.2 1592.07   351.8  1582.1   381.1 1578.03   390.9    1576
   409.6 1569.46   420.1 1567.33   429.8 1567.32   431.7 1567.59   439.6  1568.9
   449.4 1571.25   478.6 1577.36   517.6 1586.71   527.3 1589.81   546.8 1598.37
   556.6 1602.02   566.3 1604.26   585.8 1607.03   595.6 1608.95   683.3  1629.6
#Mann= 3 , 0 , 0
       0      .1       0   409.6    .045       0   431.7      .1       0
Bank Sta=409.6,431.7
XS Rating Curve= 0 ,0
Exp/Cntr=0.3,0.1

Type RM Length L Ch R = 1 ,3165.3  ,396.8,392.9,389
XS GIS Cut Line= 3
     1917762.844      421025.023     1917450.344      420912.176
     1917259.371      420836.221
#Sta/Elev= 30
       0 1629.31    19.5 1623.03    39.1 1617.09    48.9 1614.32    58.6 1612.28
    68.4 1610.64    97.7 1605.28   107.5 1603.19   117.3 1600.83     127 1598.26
   136.8 1595.32   146.6 1592.04   156.4 1588.48   175.9 1581.05   195.4  1574.3
   205.2 1570.65     215 1566.12   224.8 1561.28  231.64 1559.42   234.5 1558.64
   244.3 1558.25   254.1 1558.94   273.6 1561.08   302.9 1564.05     391 1572.73
   439.9 1577.92   449.7 1579.16   459.5 1580.87   469.3  1583.1   537.8 1599.68
#Mann= 3 , 0 , 0
       0      .1       0  231.64    .045       0   254.1      .1       0
Bank Sta=231.64,254.1
XS Rating Curve= 0 ,0
Exp/Cntr=0.3,0.1

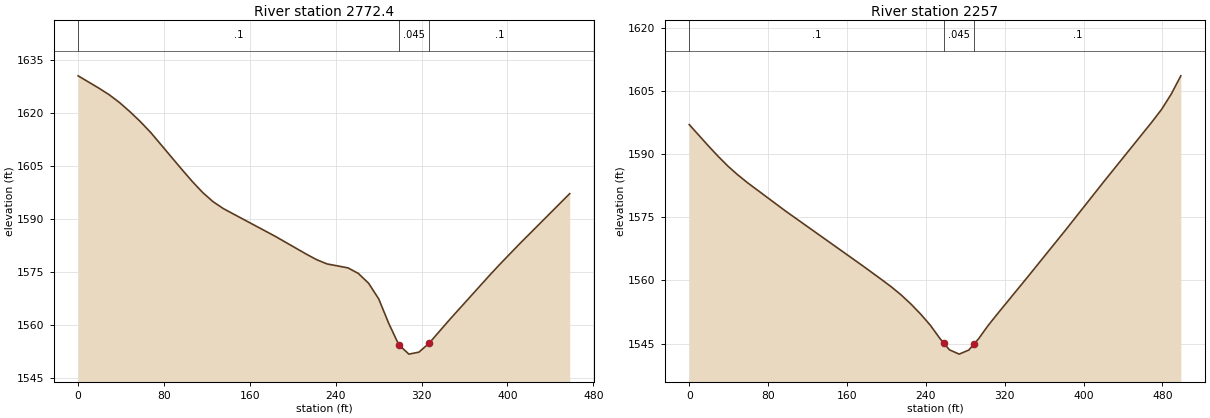
Type RM Length L Ch R = 1 ,2772.4  ,501.5,515.4,529.2
XS GIS Cut Line= 3
     1917808.417      420617.037      1917543.66      420560.613
     1917359.198      420528.061
#Sta/Elev= 30
       0  1630.5    19.3 1627.02      29 1625.14    38.7  1622.9    48.3 1620.34
      58 1617.53    67.7 1614.44    96.7 1603.98   106.4 1600.58     116 1597.48
   125.7 1594.87   135.4 1592.89   183.7 1585.05   212.7    1580   222.4 1578.42
     232 1577.24   251.4 1576.12     261 1574.57   270.7 1571.75   280.1 1567.32
   289.4 1560.42   298.8 1554.33   308.2  1551.7   317.5 1552.26   326.9 1554.74
   345.6 1561.29   383.1 1573.93   392.5    1577   411.2 1582.89     458 1597.14
#Mann= 3 , 0 , 0
       0      .1       0   298.8    .045       0   326.9      .1       0
Bank Sta=298.8,326.9
XS Rating Curve= 0 ,0
Exp/Cntr=0.3,0.1

Type RM Length L Ch R = 1 ,2257    ,583.3,574.5,565.7
XS GIS Cut Line= 2
     1917916.924      420300.197     1917565.361      419946.464
#Sta/Elev= 30
       0 1597.01    19.6 1591.91    29.3 1589.48    39.1 1587.18    48.9 1585.14
    58.7 1583.28    97.8 1576.46     176 1563.47   195.6 1560.12   205.4  1558.4
   215.1 1556.52   224.9 1554.39   234.7 1552.01   244.5 1549.37   254.2 1546.24
   258.3 1545.05     264 1543.51   273.8 1542.49   283.6 1543.46  288.58 1544.82
   293.4  1546.1   303.1 1549.26   312.9 1552.13   342.3 1560.53   381.4 1571.86
   420.5 1583.44   469.4 1597.65   479.2 1600.64   488.9 1604.24   498.7  1608.6
#Mann= 3 , 0 , 0
       0      .1       0   258.3    .045       0  288.58      .1       0
Bank Sta=258.3,288.58
XS Rating Curve= 0 ,0
Exp/Cntr=0.3,0.1