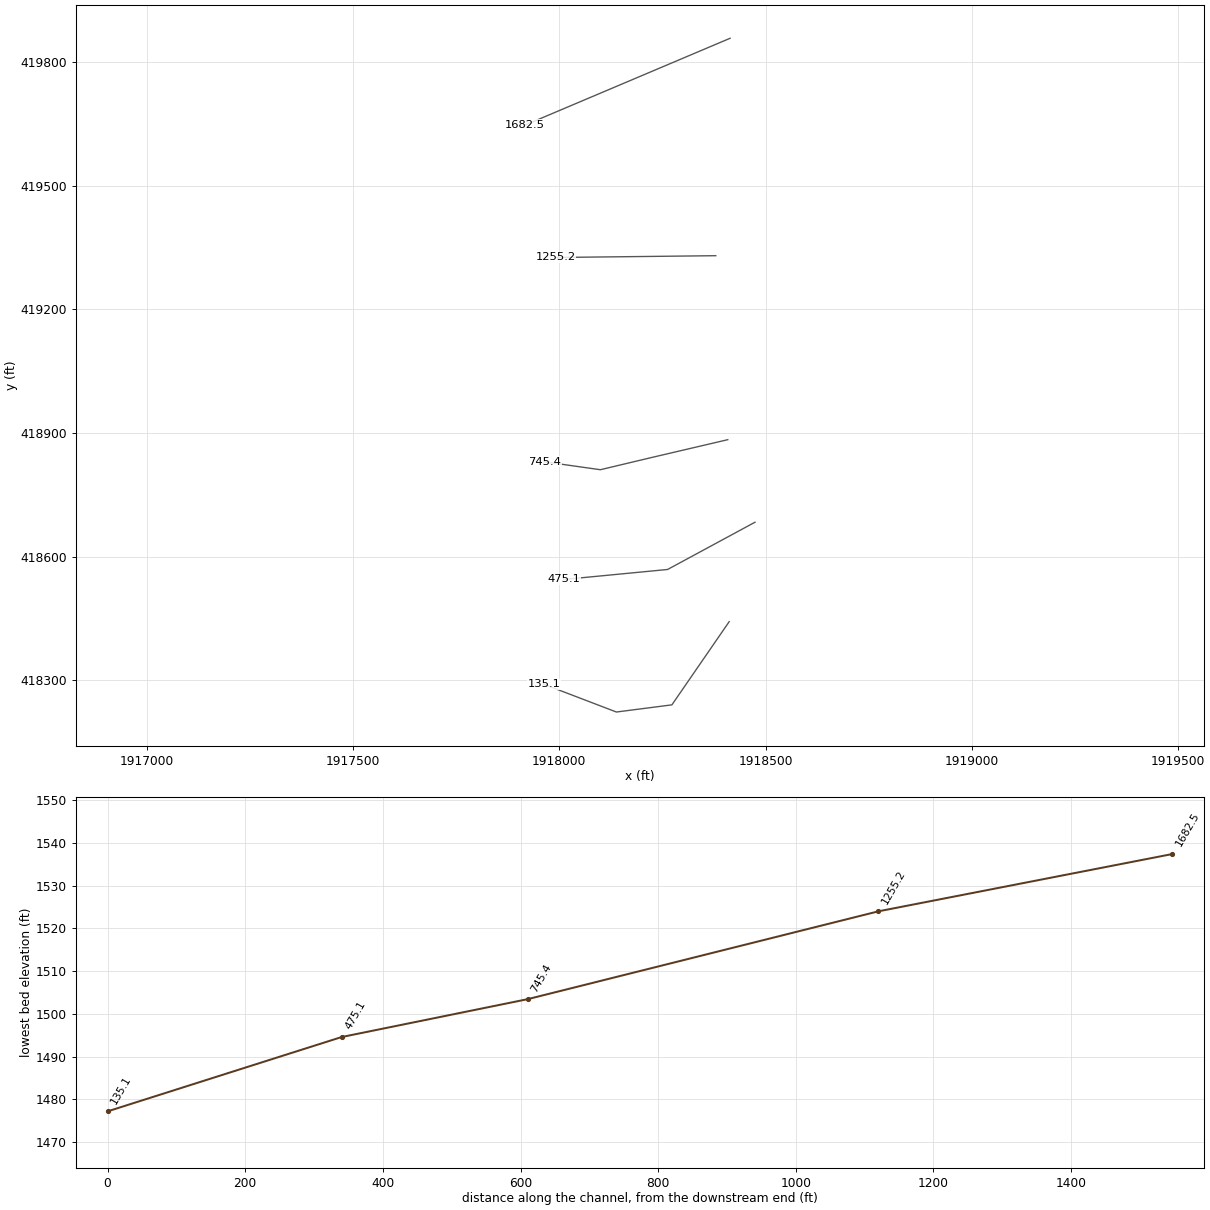
HEC-RAS study HAZELRUN.prj: HAZELRUN

--- HAZELRUN.g01 (geometry) --- (continued)

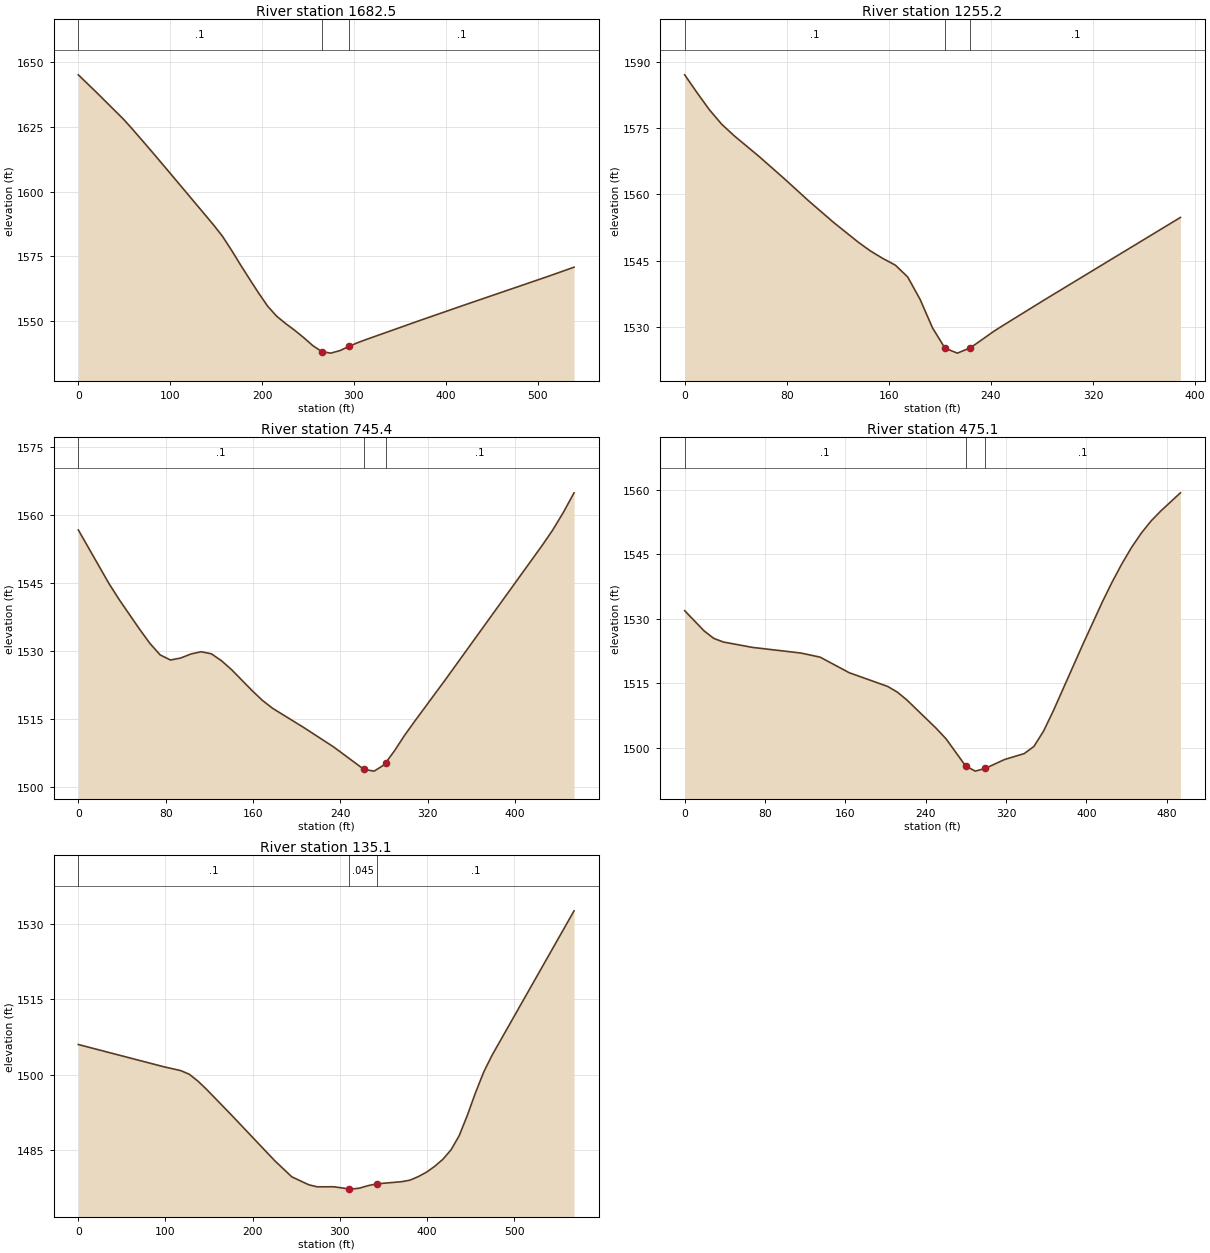
Type RM Length L Ch R = 1 ,1682.5  ,435.9,427.2,418.3
XS GIS Cut Line= 2
     1918413.885      419857.488     1917916.924      419646.985
#Sta/Elev= 28
       0 1645.22    19.6 1638.48    49.1 1628.06    58.9 1624.19    78.5 1616.13
    98.1  1607.9   147.2  1587.1     157 1582.65   166.8 1577.28   176.6 1571.61
   186.4 1566.12   196.3 1560.69   206.1 1555.63   215.9 1551.73   225.7 1548.89
   235.5 1546.28   245.3 1543.45   255.1 1540.38     265 1538.02   274.8 1537.42
   284.6 1538.37   294.4 1539.99   304.2 1541.48     314 1542.77   372.9  1550.2
     422 1556.26   510.3 1567.01   539.7 1570.71
#Mann= 3 , 0 , 0
       0      .1       0     265    .045       0   294.4      .1       0
Bank Sta=265,294.4
XS Rating Curve= 0 ,0
Exp/Cntr=0.3,0.1

Type RM Length L Ch R = 1 ,1255.2  ,504.3,509.9,514.5
XS GIS Cut Line= 2
     1918379.163      419330.145     1917990.708      419325.804
#Sta/Elev= 23
       0 1587.08     9.7 1583.03    19.4 1579.15    29.1 1575.86    38.8 1573.27
    58.3 1568.58    77.7 1563.64    97.1 1558.53   116.5 1553.68     136 1549.16
   145.7 1547.14   155.4 1545.45   165.1 1543.95   174.8 1541.26   184.5 1536.19
   194.2 1529.75     204 1525.13   213.7 1524.01   223.9 1525.21   242.8 1529.06
   252.5 1530.82   281.6 1536.02   388.5 1554.76
#Mann= 3 , 0 , 0
       0      .1       0     204    .045       0   223.9      .1       0
Bank Sta=204,223.9
XS Rating Curve= 0 ,0
Exp/Cntr=0.3,0.1

Type RM Length L Ch R = 1 ,745.4   ,273.3,270.2,267
XS GIS Cut Line= 4
     1918408.231      418883.895     1918225.719      418841.153
     1918099.468      418811.044      1917964.08      418830.197
#Sta/Elev= 30
       0 1556.65    28.1 1544.81    37.5 1541.26    56.2 1534.72    65.6 1531.61
      75 1529.07    84.4 1527.96    93.7 1528.39   103.1 1529.28   112.5 1529.78
   121.8 1529.33   131.2 1527.78   140.6 1525.77   159.3 1521.17   168.7 1519.03
   178.1 1517.27     206 1513.13   233.8 1508.78   261.6 1503.82   270.9 1503.44
   280.2 1504.85   281.5 1505.28   289.4 1507.87   298.7  1511.3     308 1514.42
   336.8 1523.83   424.7  1553.2   434.4 1556.61   444.2 1560.52     454 1564.84
#Mann= 3 , 0 , 0
       0      .1       0   261.6    .045       0   281.5      .1       0
Bank Sta=261.6,281.5
XS Rating Curve= 0 ,0
Exp/Cntr=0.3,0.1

Type RM Length L Ch R = 1 ,475.1   ,338.4,340,342.2
XS GIS Cut Line= 3
     1918474.215      418683.689      1918262.41      418569.106
     1918010.674        418544.8
#Sta/Elev= 30
       0 1531.87    19.3 1527.18    28.9 1525.44    38.5 1524.59    67.4 1523.34
   115.6 1522.03   134.9 1521.07   163.8 1517.46   202.3 1514.25   211.9 1512.93
   221.6 1511.05   250.5 1504.53   260.3 1502.09   279.7 1495.81   289.4 1494.58
   299.2  1495.2   318.6 1497.28   338.1 1498.65   347.8 1500.32   357.5 1503.92
   367.3 1508.68   396.4 1523.96   415.9 1533.88   425.6 1538.48   435.4 1542.76
   445.1 1546.59   454.8 1549.91   464.5 1552.72   474.3 1555.07   493.7 1559.26
#Mann= 3 , 0 , 0
       0      .1       0   279.7    .045       0   299.2      .1       0
Bank Sta=279.7,299.2
XS Rating Curve= 0 ,0
Exp/Cntr=0.3,0.1

Type RM Length L Ch R = 1 ,135.1   ,130.3,135.1,139
XS GIS Cut Line= 4
     1918411.715      418442.558     1918272.826      418240.735
     1918138.278      418223.374     1917962.496      418290.648
#Sta/Elev= 30
       0 1505.99      98 1501.56   117.6 1500.79   127.4 1500.06   137.2 1498.71
     147 1497.09   176.4 1491.83   225.4 1482.85     245 1479.64   264.4 1478.06
   274.1 1477.65   293.4 1477.66  310.57 1477.23   312.8 1477.19   322.5 1477.38
   332.2 1477.87   342.3 1478.24     371 1478.67   380.7 1478.98   390.1 1479.68
   399.5 1480.56   408.9 1481.72   418.3 1483.12   427.7 1485.01   437.1 1487.84
   446.5 1491.92     456 1496.48   465.4 1500.57   474.8 1503.85   568.9 1532.61
#Mann= 3 , 0 , 0
       0      .1       0  310.57    .045       0   342.3      .1       0
Bank Sta=310.57,342.3
XS Rating Curve= 0 ,0
Exp/Cntr=0.3,0.1

Chan Stop Cuts=-1
Use User Specified Reach Order=0
Composite Channel Slope=5